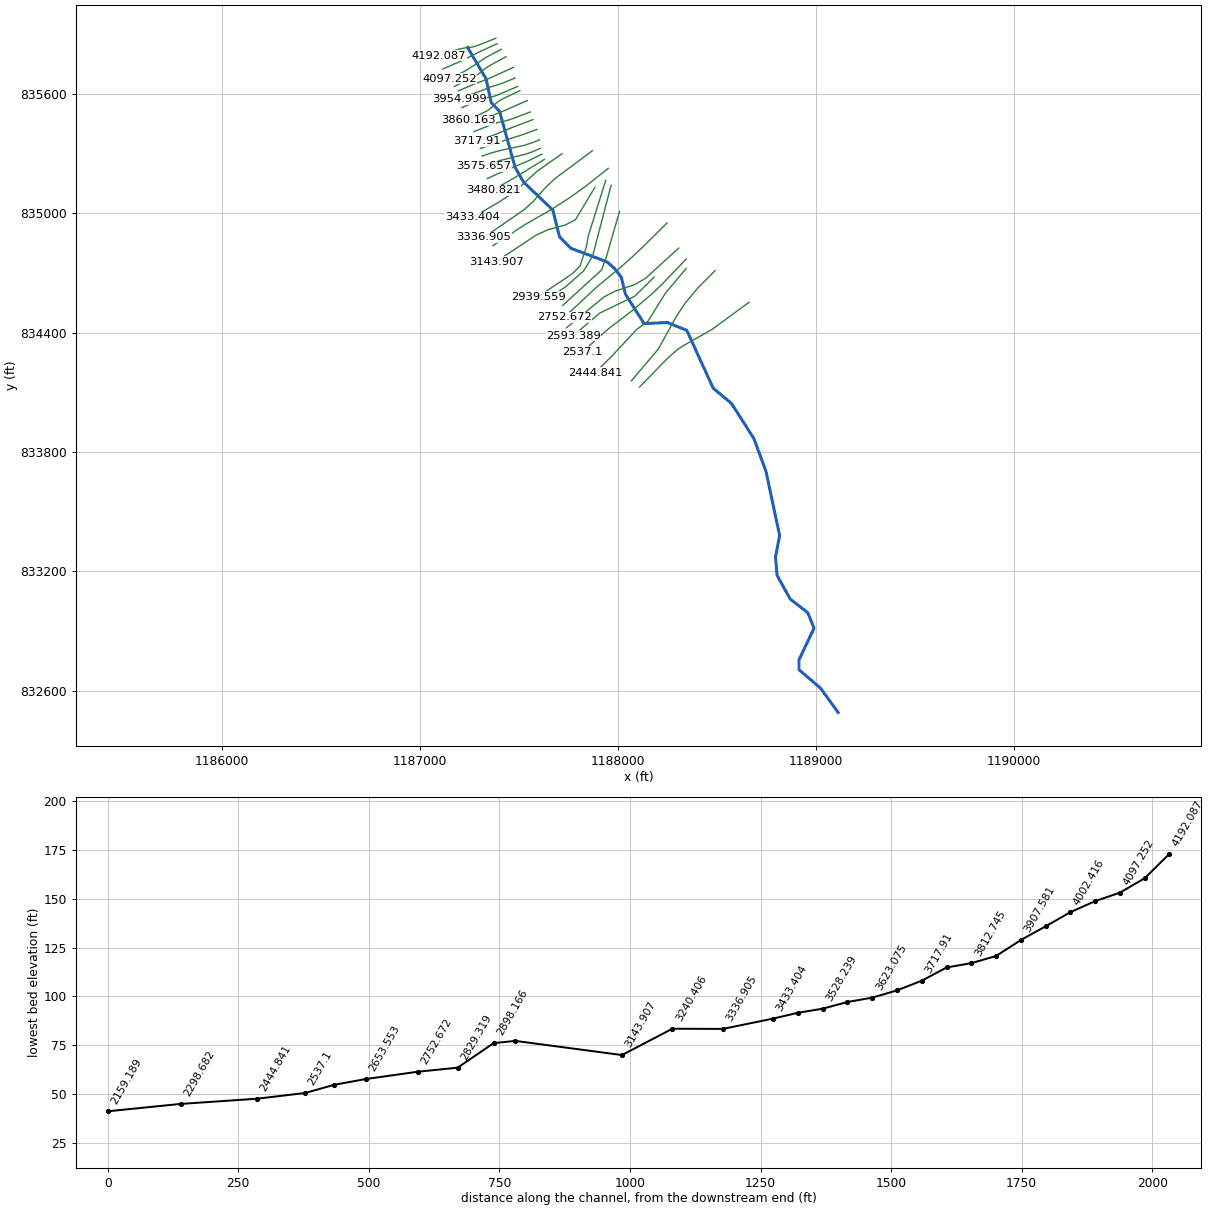
--- 25_ras.prj (project) ---

Proj Title=25
Current Plan=p01
Default Exp/Contr=0.3,0.1
English Units
Geom File=g01
Flow File=f01
Plan File=p01
Y Axis Title=Elevation
X Axis Title(PF)=Main Channel Distance
X Axis Title(XS)=Station
BEGIN DESCRIPTION:
RFD model 25 exported to HEC-RAS
END DESCRIPTION:

--- 25_ras.p01 (plan) ---

Plan Title=Plan 01
Program Version=4.10
Short Identifier=Plan 01
Geom File=g01
Flow File=f01
Subcritical Flow
Calc Critical at every XS
Secant Critical Depth

--- 25_ras.f01 (steady flow) ---

Flow Title=Flow 01
Program Version=5.01
Number of Profiles= 5
Profile Names=10yr,25yr,50yr,100yr,500yr
River Rch & RM=25,49,4192.087
   97.42  172.36  243.96  328.93  574.88
River Rch & RM=25,49,4049.834
  101.18  179.16  253.78  342.47  599.92
River Rch & RM=25,49,3907.581
  109.93  195.01  276.72  374.12  658.68
River Rch & RM=25,49,3765.328
  153.41  274.14  391.74  533.64  958.75
River Rch & RM=25,49,3623.075
  157.12  280.92  401.62   547.4   984.9
River Rch & RM=25,49,3480.821
  192.23  345.21  495.64  678.63 1236.07
River Rch & RM=25,49,3336.905
  198.36  356.48  512.16  701.75 1280.62
River Rch & RM=25,49,3240.406
   209.4  376.76  541.91  743.43 1361.15
River Rch & RM=25,49,2939.559
  227.76  410.54  591.54  813.06 1496.26
River Rch & RM=25,49,2829.319
  232.03  418.42  603.13  829.34 1527.94
River Rch & RM=25,49,2752.672
  232.64  419.55  604.78  831.67 1532.47
River Rch & RM=25,49,2593.389
  238.14  429.68  619.69  852.61  1573.3
River Rch & RM=25,49,2444.841
  278.93  505.03  730.78 1009.07 1879.97
River Rch & RM=25,49,2298.682
  280.75   508.4  735.76  1016.1 1893.81
River Rch & RM=25,49,2159.189
  309.86  562.33   815.5 1128.73 2116.38
River Rch & RM=25,49,1959.723
  323.18  587.03  852.07 1180.48 2219.08
River Rch & RM=25,49,1860.604
  329.83  599.38  870.37 1206.39 2270.58
River Rch & RM=25,49,1761.486
  415.36  758.63 1106.97 1542.37 2943.89
River Rch & RM=25,49,1662.367
  423.16   773.2 1128.67 1573.26 3006.25
River Rch & RM=25,49, 1464.13
  444.14  812.41 1187.11 1656.53 3174.69
River Rch & RM=25,49,1365.011
  451.93  826.97 1208.82  1687.5 3237.45
River Rch & RM=25,49,1166.774
  462.11     846 1237.23 1728.02 3319.68
River Rch & RM=25,49,1067.655
  483.04  885.18 1295.73 1811.55 3489.53
River Rch & RM=25,49,968.5368
  486.03  890.78 1304.09  1823.5 3513.85
River Rch & RM=25,49,869.4181
  494.39  906.45 1327.51 1856.95 3582.03
River Rch & RM=25,49,744.8112
  497.98  913.16 1337.54  1871.3 3611.29
River Rch & RM=25,49,467.5351
  502.16     921 1349.25 1888.04 3645.45
River Rch & RM=25,49,271.1879
  540.92  993.71 1458.05 2043.72  3963.9
River Rch & RM=25,49,140.0477
  546.28 1003.77 1473.12 2065.31 4008.17
River Rch & RM=25,49,       0
  547.47 1006.01 1476.47  2070.1 4018.01
Boundary for River Rch & Prof#=25,49,1
Up Type= 0
Dn Type= 2
Boundary for River Rch & Prof#=25,49,2
Up Type= 0
Dn Type= 2
Boundary for River Rch & Prof#=25,49,2
Up Type= 0
Dn Type= 2
Boundary for River Rch & Prof#=25,49,2
Up Type= 0
Dn Type= 2
Boundary for River Rch & Prof#=25,49,2
Up Type= 0
Dn Type= 2

--- 25_ras.g01 (geometry) ---

Geom Title=25
Program Version=4.10

River Reach=25,49
Reach XY= 30
1187241.22303113835834.547653437 1187334.5563325835676.214364186
1187360.38965484835557.8810650711187402.88964102835512.881077141
1187481.22294319835231.2144914271187523.72292861835157.881178543
1187671.94170344835016.9370859271187705.68695822834882.304395333
 1187763.4610002834824.5303533081187945.27930892 834756.56089215
1187984.36174905834722.5761615341188017.73686817834679.665294155
1188038.72276106834593.7146636551188132.88939577834446.214704528
1188251.22269452834451.2146996261188348.72266471834412.048041716
1188482.05595052834121.2147904341188574.55592111 834044.54814373
1188687.88921607833867.8815260231188748.72252676833703.714906096
1188817.88916373833380.3816662881188797.05965587833271.249434695
1188805.09299287833179.6693927051188871.36321756833060.722835645
1188959.72351706832992.7533744571188992.00901109832914.588494077
 1188915.5433673832754.860260308 1188915.5433673832705.582400948
1189024.55574754832612.8818870931189113.72238445832490.381920695

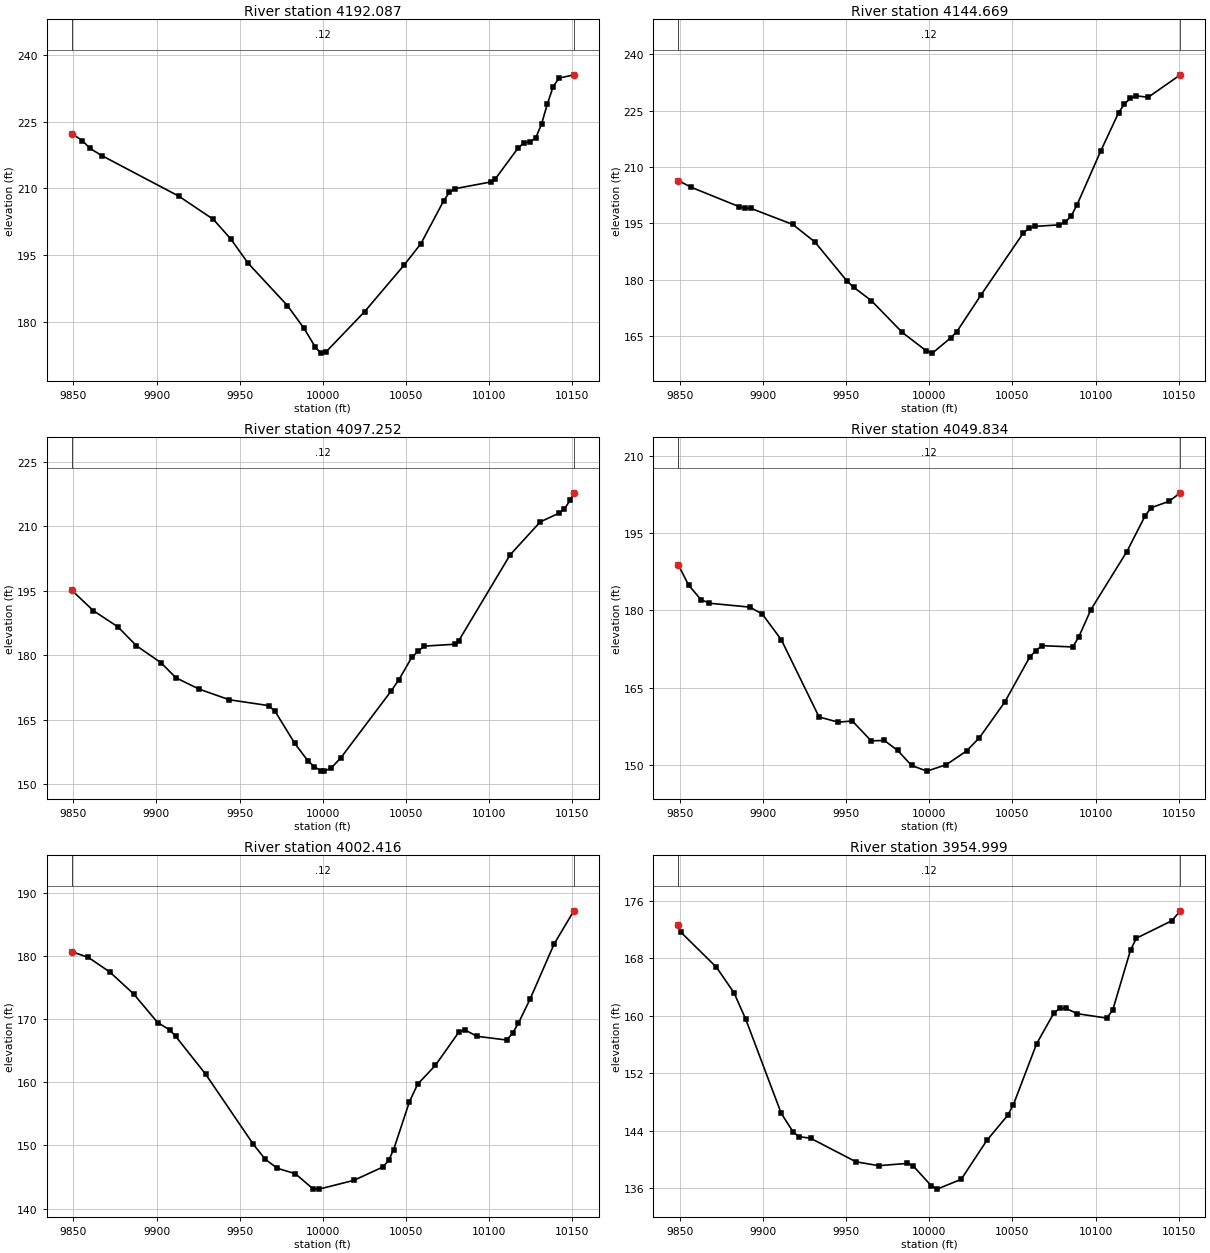
Type RM Length L Ch R = 1 ,4192.087,47.417700,47.417700,47.417700
XS GIS Cut Line= 6
1187384.07539079835880.6159778521187285.92473024835842.283271854
1187261.03517745835836.0406396951187223.23138134835831.501044355
1187196.50544193835825.8202697471187096.34808471835792.866793337
#Sta/Elev= 30
9849.036222.29539855.423220.7306 9860.06218.96279867.166217.34719913.331208.2471
9934.211202.99959944.651198.60359955.073193.1414 9978.75183.59959988.704178.4937
 9995.32174.37459998.628172.907610001.92173.176110025.15 182.24610048.69192.6307
10058.96197.522710072.65207.161610076.07 209.06810079.49209.917610101.42211.4538
 10103.7212.095310117.61219.152410121.09220.236810124.56220.479110128.04221.3335
10131.52224.416110134.99228.929210138.47 232.80410141.95234.781410150.97235.5368
#Mann= 3 , 0 , 0
9849.036    0.12       09849.036    0.12       010150.97    0.12       0
#XS Ineff= 2 , 0
       0                               0
Bank Sta=9849.036,10150.97
Exp/Cntr=0.3,0.1

Type RM Length L Ch R = 1 ,4144.669,47.417700,47.417700,47.417700
XS GIS Cut Line= 6
1187390.50485424835853.6860473421187294.86477979835809.342250385
1187255.08582702835789.2268108421187253.28681067835788.353002966
1187209.36429337835766.5576944931187116.67213868835726.555793567
#Sta/Elev= 30
9849.004206.38649856.462204.65999885.393199.46279889.009198.99519892.625198.9832
 9917.94194.67549931.205190.01419950.487 179.6339954.592177.92919965.127174.4138
9983.673165.97049998.215161.020310001.87160.4197   10013164.520810016.52166.1108
10031.17 175.94410056.65192.471610060.22193.747510063.79194.171910078.09194.5795
10081.66195.311910085.23  196.8310088.81199.8542 10103.1214.219810113.82224.3976
10117.39226.793110120.96228.251310124.54 228.93310131.68228.565110150.99234.5346
#Mann= 3 , 0 , 0
9849.004    0.12       09849.004    0.12       010150.99    0.12       0
#XS Ineff= 2 , 0
       0                               0
Bank Sta=9849.004,10150.99
Exp/Cntr=0.3,0.1

Type RM Length L Ch R = 1 ,4097.252,47.417700,47.417700,47.417700
XS GIS Cut Line= 6
1187411.54079129835825.3702444561187331.39011427835783.041899233
1187259.49480449835735.0028779031187230.27840963835717.390462526
1187190.23431548835696.6125754011187148.85372402835677.469717891
#Sta/Elev= 30
9849.047195.09149861.937190.36669876.778186.58489887.908182.19139902.749178.2386
9911.633174.75829925.684172.1021 9943.79169.64119967.364168.28759971.293 166.967
 9983.08159.53899990.938155.49879994.866154.08599998.795153.1584   10001153.0557
10005.08  153.7810010.88156.165210041.19171.715610045.81174.325310053.48179.4664
10057.31180.926810061.11182.105510079.59182.552610081.62183.266710112.69 203.333
10130.76210.970210141.83212.965310145.22213.923610148.84 216.05210150.98217.7306
#Mann= 3 , 0 , 0
9849.047    0.12       09849.047    0.12       010150.98    0.12       0
#XS Ineff= 2 , 0
       0                               0
Bank Sta=9849.047,10150.98
Exp/Cntr=0.3,0.1

Type RM Length L Ch R = 1 ,4049.834,47.417700,47.417700,47.417700
XS GIS Cut Line= 6
1187435.16020615835788.2806244111187355.02237664835744.540324892
1187323.62111203835723.382923551 1187292.2289921835698.760729222
1187269.13243628835684.2494222991187174.13153025835638.242225305
#Sta/Elev= 30
9849.025188.88519855.205184.94339862.591182.11369867.623181.39439892.138  180.63
9899.618 179.2659910.981   174.39933.707 159.2759945.281158.25669953.683158.4968
9965.061154.62419972.973154.70069981.025152.75119989.352149.83499998.581148.7367
10010.26149.9911 10022.4152.655810030.15155.228910045.39162.163810060.42170.9294
10064.12172.186610067.82173.1362 10086.3172.887710089.94174.854310097.16180.1245
10118.85191.450410129.69198.3107 10133.3199.950510144.15   201.210150.97202.8614
#Mann= 3 , 0 , 0
9849.025    0.12       09849.025    0.12       010150.97    0.12       0
#XS Ineff= 2 , 0
       0                               0
Bank Sta=9849.025,10150.97
Exp/Cntr=0.3,0.1

Type RM Length L Ch R = 1 ,4002.416,47.417700,47.417700,47.417700
XS GIS Cut Line= 6
1187473.44315489835734.6081682331187344.67658102 835676.37237095
1187336.62075764835673.1833661151187334.72339103835672.550910635
1187281.21958524835653.082856634 1187195.6326001 835616.56644043
#Sta/Elev= 30
9849.013180.65259858.918179.76639871.849177.45489886.252173.96739900.655169.4455
9907.856168.29889911.457167.28329929.461161.30179958.267150.15849965.468147.7859
 9972.67146.37669983.472 145.5299994.195143.10659997.724143.082610018.67144.4706
10036.12146.581510039.61147.648610042.54149.298910052.13156.935710057.07159.6976
10067.75162.685710082.02168.005310085.59168.267510092.72167.267410110.56166.6815
10114.12167.740310117.69169.368610124.82173.244310139.09181.861110150.99187.1264
#Mann= 3 , 0 , 0
9849.013    0.12       09849.013    0.12       010150.99    0.12       0
#XS Ineff= 2 , 0
       0                               0
Bank Sta=9849.013,10150.99
Exp/Cntr=0.3,0.1

Type RM Length L Ch R = 1 ,3954.999,47.417800,47.417800,47.417800
XS GIS Cut Line= 6
1187480.40139783835680.5905226351187409.57387311 835651.55731465
1187347.58963834835633.4297876591187323.88264688835621.807952717
1187264.34501469835600.3583055111187198.55223792835573.411254335
#Sta/Elev= 30
9849.062172.58459850.703171.61789871.978166.76979882.615163.18699889.707159.4793
9910.981146.41659918.073143.84759921.618143.16529928.599142.94589955.945139.6639
9969.618139.11889986.709139.43859990.127 139.14610001.08136.357210004.74135.8572
10019.23  137.2310034.62142.637310047.13146.117310050.62147.624510064.57 156.098
10075.03160.407810078.52161.016210082.04161.038110089.13160.278710106.86159.6681
 10110.4160.836910121.04169.141710124.58170.798310145.85173.219310150.98174.6057
#Mann= 3 , 0 , 0
9849.062    0.12       09849.062    0.12       010150.98    0.12       0
#XS Ineff= 2 , 0
       0                               0
Bank Sta=9849.062,10150.98
Exp/Cntr=0.3,0.1

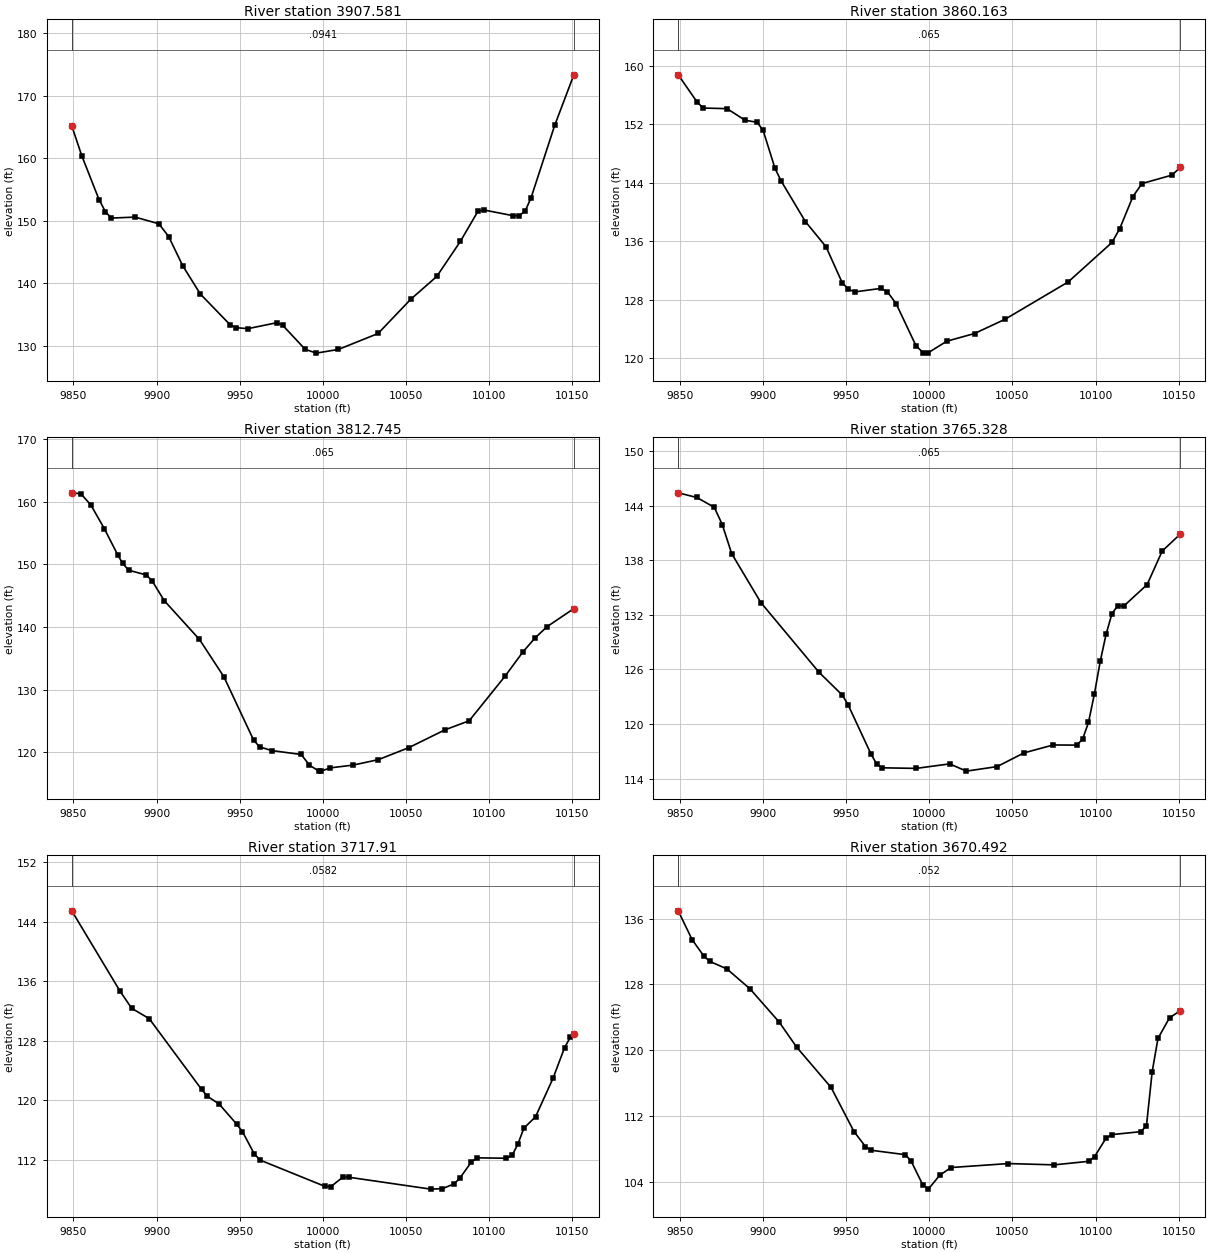
Type RM Length L Ch R = 1 ,3907.581,47.417700,47.417700,47.417700
XS GIS Cut Line= 6
1187494.25844666835638.5172226031187390.14573963835594.211198862
1187369.94987883 835587.74188697 1187339.9231355835582.264515748
1187317.02377024835575.4438015521187212.28063784835532.606149999
#Sta/Elev= 30
9849.029165.16029855.042160.38759865.413 153.3919869.305151.4192 9872.87150.4294
9887.132150.58419901.395149.51679907.306147.47889915.684142.84079926.353 138.297
9944.181133.40769947.747132.92619954.878132.7642 9972.35133.71349975.795133.3285
9989.385 129.4679996.063128.856710009.39129.447610033.23131.9926 10052.8137.4357
10068.52141.1003 10082.7146.690510093.33151.536310096.87151.7217 10114.6150.8007
10118.14150.826810121.69151.541710125.23153.663110139.47165.248810150.97173.3091
#Mann= 3 , 0 , 0
9849.029  0.0941       09849.029  0.0941       010150.97  0.0941       0
#XS Ineff= 2 , 0
       0                               0
Bank Sta=9849.029,10150.97
Exp/Cntr=0.3,0.1

Type RM Length L Ch R = 1 ,3860.163,47.417700,47.417700,47.417700
XS GIS Cut Line= 6
1187505.62974424835617.3162114561187414.39749501835574.140959356
 1187389.1491872835557.7538319511187360.16985586835530.500074964
1187339.27529271835515.6190354671187244.63260574835469.362671723
#Sta/Elev= 30
9849.055158.73069860.414155.00669864.017154.19189878.429154.10629889.238152.5246
9896.444152.24479900.047151.16929907.253145.93499910.856144.25119925.522138.6677
9937.935135.22459947.599130.34089951.359 129.413 9955.27129.06319970.915129.5386
9974.827129.08149980.111127.43639991.942121.73219996.254120.7399    9999120.6925
10010.51122.319610027.21123.373410045.55125.318510083.51130.419810109.85135.8157
10114.53137.706510122.44142.087510127.87143.8638 10145.9145.024710150.95146.0789
#Mann= 3 , 0 , 0
9849.055   0.065       09849.055   0.065       010150.95   0.065       0
#XS Ineff= 2 , 0
       0                               0
Bank Sta=9849.055,10150.95
Exp/Cntr=0.3,0.1

Type RM Length L Ch R = 1 ,3812.745,47.417700,47.417700,47.417700
XS GIS Cut Line= 6
1187542.96092266835567.8070605941187418.48871224835513.193053758
1187405.32717268835508.2360732981187395.16312084 835504.55579313
1187327.58895379 835471.921805241187267.13183196835445.117321159
#Sta/Elev= 30
9849.009161.38499854.495 161.2389860.465 159.4559868.631155.66219876.796151.4143
9879.574150.17659883.157149.06259893.905148.28839897.488147.29199904.653144.1926
 9925.79138.0233 9940.48132.07899958.394121.96919961.977120.90549969.142120.3137
9987.011119.68279991.979117.98069997.528117.0494    9999117.030910004.49117.5482
10018.29117.996310033.38118.857810051.65120.763610073.51123.616110088.03125.0539
10109.57132.147810120.33 136.01510127.51138.213110134.86 140.05310150.99142.9296
#Mann= 3 , 0 , 0
9849.009   0.065       09849.009   0.065       010150.99   0.065       0
#XS Ineff= 2 , 0
       0                               0
Bank Sta=9849.009,10150.99
Exp/Cntr=0.3,0.1

Type RM Length L Ch R = 1 ,3765.328,47.417700,47.417700,47.417700
XS GIS Cut Line= 6
1187558.19592623835510.1808825791187459.52028931835473.147230475
1187433.17981874835465.6516187911187394.10537146835457.206073878
1187371.36189222835450.2710428181187273.31546763835411.568997931
#Sta/Elev= 30
9849.032145.40059860.157144.8899 9870.67143.81759875.535141.90529881.183138.7167
9898.704133.34729933.747125.67059947.764 123.1679951.268122.07829964.997116.6781
9968.408115.58949971.819115.1837 9992.11115.120310012.25115.614410022.34114.8193
10040.82115.317910056.95116.823410074.59117.6958 10088.7 117.67510092.23118.3375
10095.75120.167810099.28123.273110102.81126.869710106.33129.856810109.86132.1135
10113.39133.004910116.92132.943710131.02135.317610140.09139.001610150.98140.8703
#Mann= 3 , 0 , 0
9849.032   0.065       09849.032   0.065       010150.98   0.065       0
#XS Ineff= 2 , 0
       0                10053.52       0
Bank Sta=9849.032,10150.98
Exp/Cntr=0.3,0.1

Type RM Length L Ch R = 1 , 3717.91,47.417700,47.417700,47.417700
XS GIS Cut Line= 6
 1187571.6717434835471.771775059 1187459.7950918835429.640183567
1187431.75574419835417.7780412011187429.92914039835416.963474705
1187392.55273066 835401.312288741187289.95404532835363.132858338
#Sta/Elev= 30
9849.008145.44739878.043134.65969885.054 132.3579895.572130.97399927.124121.4593
9930.629120.53859937.641119.50429948.158116.81679951.664115.79739958.675112.8604
9962.181111.988410001.28108.450710004.84108.423910011.95109.664610015.51109.6825
10064.93108.081410071.93108.145810078.93108.785610082.43109.552710089.43111.7457
10092.93112.282810110.44112.226110113.94112.629210117.44114.188510120.94 116.273
10127.94117.789210138.44122.947610145.44127.088310148.94128.495610150.99128.9612
#Mann= 3 , 0 , 0
9849.008  0.0582       09849.008  0.0582       010150.99  0.0582       0
#XS Ineff= 2 , 0
       0                10039.93       0
Bank Sta=9849.008,10150.99
Exp/Cntr=0.3,0.1

Type RM Length L Ch R = 1 ,3670.492,47.417700,47.417700,47.417700
XS GIS Cut Line= 6
 1187591.7097057835422.327760102 1187518.2286512835395.592421931
1187449.80609234 835373.861054761187447.88119298835373.318134483
1187372.85471146835349.6433111321187305.41115887835326.451304258
#Sta/Elev= 30
9849.016136.94399857.359133.44279864.341131.46699867.832130.81099878.306 129.882
9892.271127.44069909.727123.42139920.201120.38289940.953115.47429954.722110.1149
9961.607 108.2939965.049107.83959985.703107.29929989.146106.5006 9996.03103.6589
9999.468103.115510006.33104.815410013.22105.743310047.62106.223210075.14106.0648
10095.92106.496310099.39107.057510106.33109.3139 10109.8109.744910127.14110.0963
10130.61110.788810134.08117.396410137.55121.431910144.49123.939110150.99124.8063
#Mann= 3 , 0 , 0
9849.016   0.052       09849.016   0.052       010150.99   0.052       0
#XS Ineff= 2 , 0
       0                10040.83       0
Bank Sta=9849.016,10150.99
Exp/Cntr=0.3,0.1

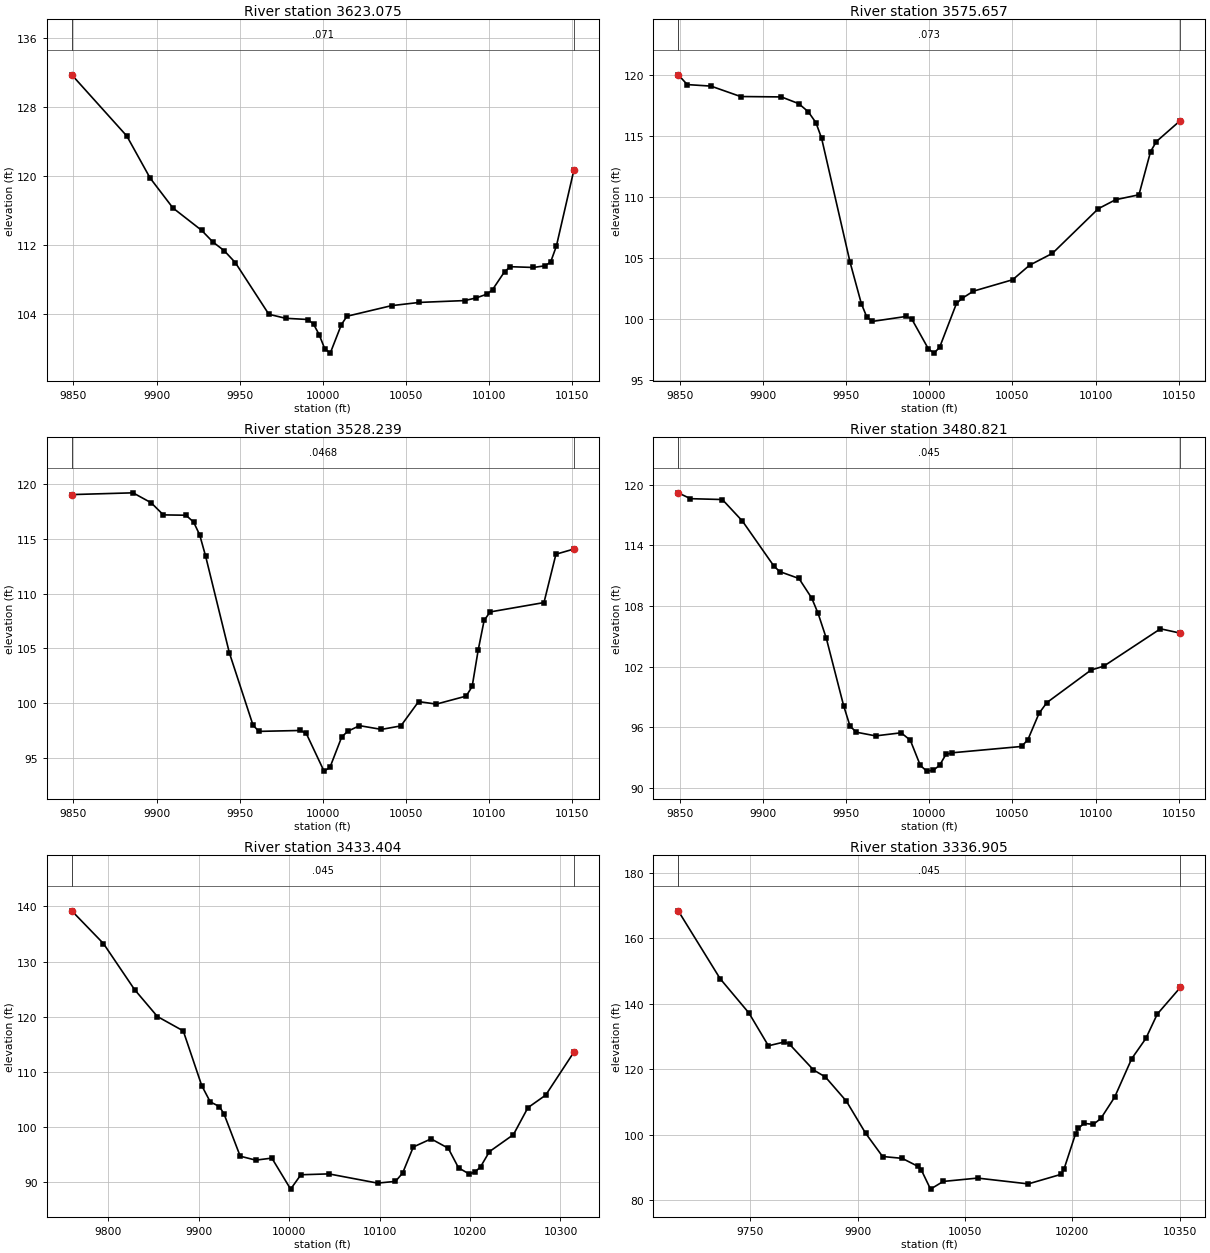
Type RM Length L Ch R = 1 ,3623.075,47.417800,47.417800,47.417800
XS GIS Cut Line= 6
1187604.92658077835369.8390280271187563.02846587835353.756658946
1187525.01749776835341.824492802 1187401.4697358835315.494874049
1187359.56504868 835303.590694811187314.74993288835288.344507762
#Sta/Elev= 30
9849.034131.72919882.132124.6252 9896.14119.74679909.894 116.2659927.088113.6789
 9933.96112.30929940.679111.31529947.397109.92389967.552103.9273 9977.63103.4601
9991.066103.31969994.426 102.7859997.785101.573510001.14 99.933310004.49 99.4152
10011.19102.731210014.54103.697910041.34104.927810058.08105.303310085.33105.5175
10092.15105.821310098.97106.279810102.08106.7873 10109.3108.866210112.76109.4498
10126.62109.362210133.55109.550710137.02109.987110140.48111.839710150.98120.6503
#Mann= 3 , 0 , 0
9849.034   0.071       09849.034   0.071       010150.98   0.071       0
#XS Ineff= 2 , 0
       0                10038.68       0
Bank Sta=9849.034,10150.98
Exp/Cntr=0.3,0.1

Type RM Length L Ch R = 1 ,3575.657,47.417700,47.417700,47.417700
XS GIS Cut Line= 6
 1187608.5696531835326.9547779491187567.22719332835309.493466938
 1187535.8282247835298.3562656441187406.68494933835266.289112273
1187363.31408038835252.3508934711187321.06800197835236.509220852
#Sta/Elev= 30
9849.018119.98099854.462119.18139868.708119.05749886.516118.2042 9911.05118.1715
9921.493117.62029927.213116.95929931.842116.06139935.254114.78199952.311 104.661
9959.125101.25419962.487100.1264 9965.8599.791969986.026100.19689989.388100.0056
9999.47897.5390710002.8697.1935710006.2397.6700310016.37101.264810019.75 101.678
 10026.5102.266410050.15103.202910060.29104.389510074.07105.363810101.64 109.018
10112.08109.7565 10126.1110.1586 10133.1113.698110136.61114.520110150.98116.2369
#Mann= 3 , 0 , 0
9849.018   0.073       09849.018   0.073       010150.98   0.073       0
#XS Ineff= 2 , 0
       0                10033.37       0
Bank Sta=9849.018,10150.98
Exp/Cntr=0.3,0.1

Type RM Length L Ch R = 1 ,3528.239,47.417700,47.417700,47.417700
XS GIS Cut Line= 6
1187617.02657554835297.877933444 1187546.6542449835263.792430179
1187480.49582497835235.9162278841187478.62772128835235.201953006
1187413.40922626835207.9548412731187341.11027181835175.344324634
#Sta/Elev= 30
9849.016119.06479885.857119.22599896.794118.31359904.085117.20939917.719 117.176
9922.312116.54559925.957 115.3799929.547113.41629943.787104.59929958.02897.97556
9961.58897.408919986.50997.49204 9990.0797.2155510000.7393.7740310004.2894.10885
10011.3996.9035610014.9597.4118410022.0697.9327510035.25 97.590410046.9597.90901
10057.61100.133610068.2899.9033310086.23100.635510089.83101.516510093.43104.8229
10097.03 107.55510100.63108.332810133.02109.189410140.22 113.61110150.99114.0835
#Mann= 3 , 0 , 0
9849.016  0.0468       09849.016  0.0468       010150.99  0.0468       0
#XS Ineff= 2 , 0
       0                10020.61       0
Bank Sta=9849.016,10150.99
Exp/Cntr=0.3,0.1

Type RM Length L Ch R = 1 ,3480.821,47.417700,47.417700,47.417700
XS GIS Cut Line= 5
1187629.50023315835271.5998679811187501.36627388835193.618768832
1187499.69635744835192.5181421541187494.08469206835189.074970152
1187370.14572374835116.917820653
#Sta/Elev= 30
9849.002119.20169856.331118.62259875.534118.53859887.616116.40679906.549111.9542
  9910.1111.40829921.622 110.7289929.303108.78639933.144107.26889938.102104.7955
9948.50798.134579952.34796.118449956.18895.52384 9967.7195.162019983.07295.46595
9988.58894.733589994.59492.248629998.43591.6752610002.3291.7514810006.1792.24021
10009.9993.3222110013.79 93.490310055.5594.1154810059.3494.7964810066.0497.39777
10070.7398.45426 10097.3101.6726 10104.9102.051810139.06 105.753   10151105.3233
#Mann= 3 , 0 , 0
9849.002   0.045       09849.002   0.045       0   10151   0.045       0
#XS Ineff= 2 , 0
       0                10014.49       0
Bank Sta=9849.002,10151
Exp/Cntr=0.3,0.1

Type RM Length L Ch R = 1 ,3433.404,96.498900,96.498900,96.498900
XS GIS Cut Line= 6
1187717.93224111835300.0742513391187593.35909426835212.675603032
1187502.88193923835130.6681340491187461.22785777835097.636028931
1187405.88990471835060.4986471981187266.88430059834980.032720163
#Sta/Elev= 30
9759.942139.21279794.982133.26589829.298124.92959854.578120.03219883.146117.4236
9903.552107.5009 9912.96104.54759923.125103.69269928.207102.34439946.05894.69201
9963.24293.97293 9981.03 94.3423 10001.888.7132210013.1291.3202210044.0491.47759
10097.8589.8069310117.6190.1184610125.5191.6142510137.3696.36121   1015797.83278
10175.95 96.138110187.3392.57768 10198.791.4988710205.0791.7605210211.6192.74107
10221.4495.5146410247.9898.59762   10264103.490510283.65105.772110314.76113.5563
#Mann= 3 , 0 , 0
9759.942   0.045       09759.942   0.045       010314.76   0.045       0
#XS Ineff= 2 , 0
       0                10016.25       0
Bank Sta=9759.942,10314.76
Exp/Cntr=0.3,0.1

Type RM Length L Ch R = 1 ,3336.905,96.498800,96.498800,96.498800
XS GIS Cut Line= 6
1187871.15405528835314.6954408791187682.86310412  835175.2982855
1187634.58381194835129.4757261471187570.74747546835058.321564659
1187526.11164959835018.373081869 1187323.8555494834879.409649818
#Sta/Elev= 30
 9649.06 168.4349707.677147.69219747.924 137.2159775.117127.21239797.539128.3857
9804.664127.68139838.124119.84439854.855117.66899884.192110.27539910.888100.5388
9934.717 93.39519962.10292.836779984.22190.380299988.61289.4026710001.7483.43151
10019.4785.7801710067.5886.8034310138.4185.0308910184.3687.9556210188.4389.60347
10204.43   100.310208.36101.980710216.22103.500410229.43103.221210239.82105.0042
10259.18111.539410282.98123.276810302.74129.443810318.68 136.87910350.93145.0223
#Mann= 3 , 0 , 0
 9649.06   0.045       0 9649.06   0.045       010350.93   0.045       0
#XS Ineff= 2 , 0
       0                10027.68       0
Bank Sta=9649.06,10350.93
Exp/Cntr=0.3,0.1

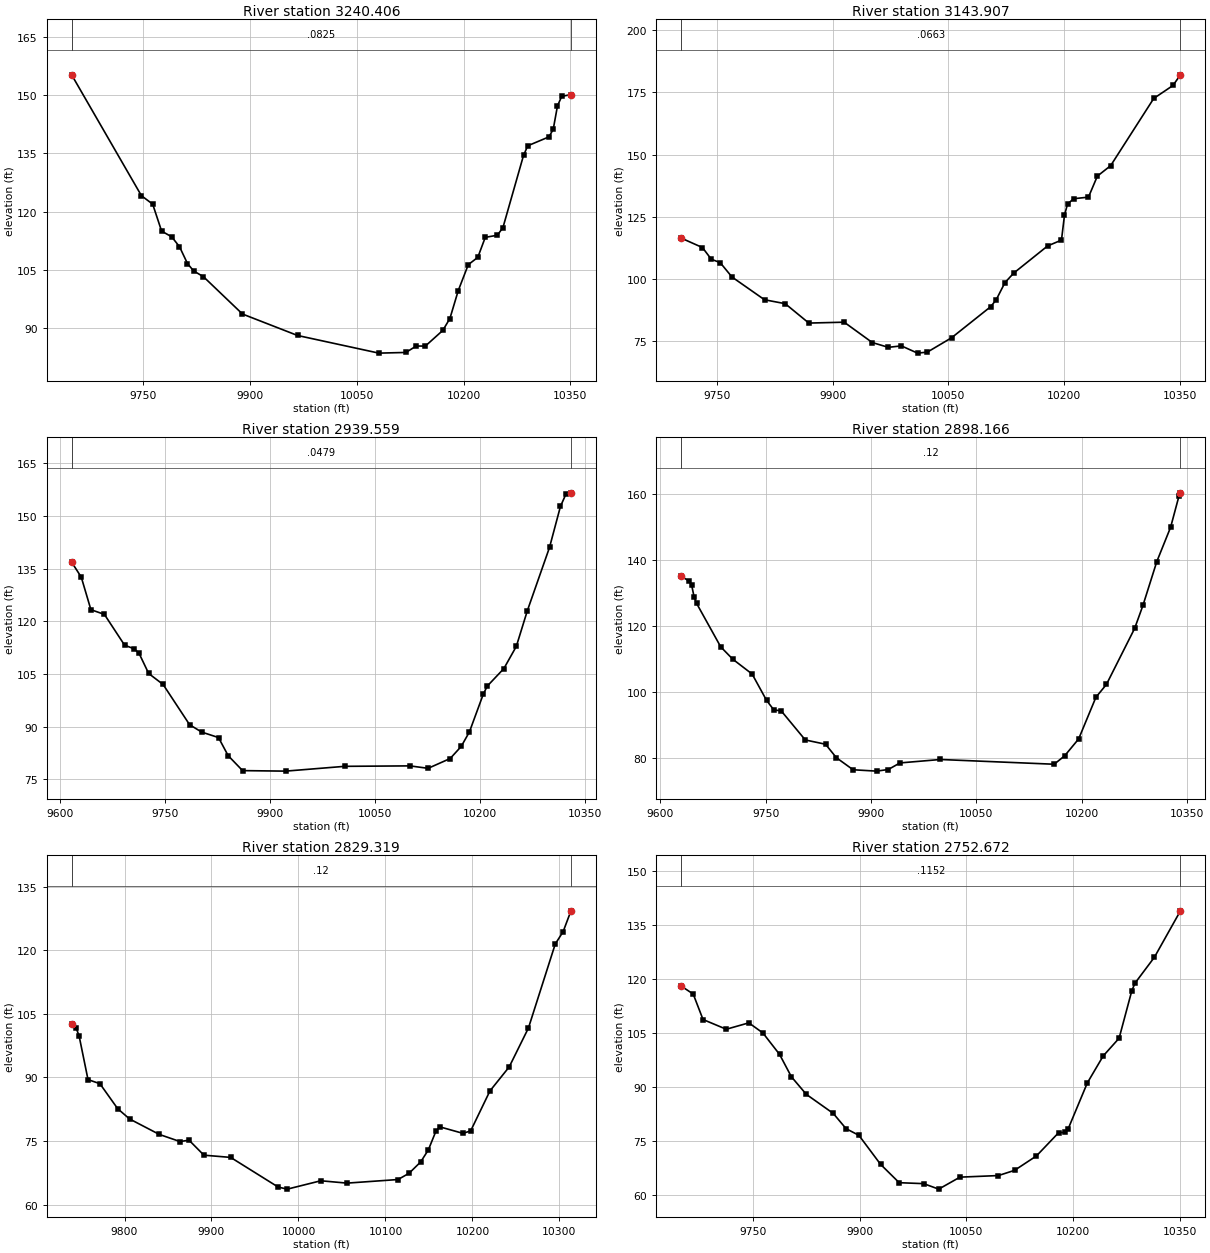
Type RM Length L Ch R = 1 ,3240.406,96.498900,96.498900,96.498900
XS GIS Cut Line= 6
1187952.49931319835226.6642016851187836.93245305835136.280210827
1187756.57931628835078.5339554721187658.06891684835015.573930024
1187532.68508126834944.8767318961187369.47097032 834837.57696844
#Sta/Elev= 30
9649.038155.28049747.147124.12129762.988121.93639775.483115.00229789.752113.5067
9800.662110.96829811.905106.61769820.533 104.7269834.393103.22199889.21693.60818
9966.61888.08007 10080.983.5305210118.96 83.704910133.4585.3630510146.2585.34378
10170.7789.3809210180.7792.4554110192.5599.6638210206.61106.333410220.03108.2315
 10230.5113.382610247.52113.921910255.37115.914110284.25134.487310290.22136.9862
10320.08 139.28810326.06141.254210332.03147.3013   10338149.732210350.97 150.184
#Mann= 3 , 0 , 0
9649.038  0.0825       09649.038  0.0825       010350.97  0.0825       0
#XS Ineff= 2 , 0
       0                10032.75       0
Bank Sta=9649.038,10350.97
Exp/Cntr=0.3,0.1

Type RM Length L Ch R = 1 ,3143.907,204.347800,204.347800,204.347800
XS GIS Cut Line= 6
1187884.28881449 835130.857372941187786.01610282834967.897137001
1187732.00685284834940.7684421241187648.02898532834918.320391178
1187590.09172225834892.5801386091187384.79751009834757.156373456
#Sta/Elev= 30
9703.625116.39769731.288112.57599742.782107.86769754.276106.5085  9769.6100.7144
9811.74491.562499838.56389.984279869.21282.178069915.02982.532779951.403 74.3491
9972.20272.409529989.15472.9960810010.1470.0784110022.8270.4816110054.2676.26096
 10104.9 88.767310112.0891.5449710123.4598.4685910134.82102.301310178.76113.2301
10196.72115.579710200.64 125.65910204.63130.124110212.61132.240810231.71132.8664
10243.24141.328710260.48145.544610316.34172.602810341.25177.818210350.96182.1068
#Mann= 3 , 0 , 0
9703.625  0.0663       09703.625  0.0663       010350.96  0.0663       0
#XS Ineff= 2 , 0
       09924.692        10030.39       0
Bank Sta=9703.625,10350.96
Exp/Cntr=0.3,0.1

Type RM Length L Ch R = 1 ,2939.559,41.393500,41.393500,41.393500
XS GIS Cut Line= 6
1187939.13763803835166.2201604791187850.77733853834885.846133123
1187841.24636441834830.9912923231187809.58075499834735.994464094
 1187770.9379774834696.8149812771187597.59109562834581.682794327
#Sta/Elev= 30
9617.002136.81579630.758132.55989644.518123.28479663.783121.95089692.677113.1766
9706.436112.13259713.316110.85749727.076105.11859747.715101.98229785.55490.52893
9802.75388.437469826.83386.870079840.59281.724329861.23277.459249922.76177.31419
10007.1978.6793510100.2678.8075310126.2778.1124310157.7880.9050710173.5384.33824
10185.3588.5136510205.0499.2056910210.76101.525510234.48106.515510252.27112.8342
10268.05123.005810299.71141.022410315.32 152.69310323.19156.213710330.35156.5621
#Mann= 3 , 0 , 0
9617.002  0.0479       09617.002  0.0479       010330.35  0.0479       0
#XS Ineff= 2 , 0
       09955.489        10070.61       0
Bank Sta=9617.002,10330.35
Exp/Cntr=0.3,0.1

Type RM Length L Ch R = 1 ,2898.166,68.846400,68.846400,68.846400
XS GIS Cut Line= 6
1187966.26437414835141.2635632571187875.60825893834795.570914611
1187859.33221725834761.9337618351187826.78013393834709.850428507
1187737.03834943834631.3263670591187624.71783173834556.726197105
#Sta/Elev= 30
9629.762 135.0479641.431133.61249644.871132.28439648.311128.76059651.751126.8855
 9686.15113.7355 9703.35109.99739730.869 105.5179751.50897.523129761.82894.65544
9772.14894.418049806.54785.594989835.38984.299369850.80980.230789874.62976.58462
 9908.06 76.17289924.69176.659029941.32178.651089998.828 79.687710160.8778.25604
10175.7680.7882310195.7585.9071710220.3598.5104710235.27102.370910275.49119.3212
10287.31126.2856   10307139.507210326.69149.902410338.51159.284510340.67160.2907
#Mann= 3 , 0 , 0
9629.762    0.12       09629.762    0.12       010340.67    0.12       0
#XS Ineff= 2 , 0
       09957.905        10073.37       0
Bank Sta=9629.762,10340.67
Exp/Cntr=0.3,0.1

Type RM Length L Ch R = 1 ,2829.319,76.647300,76.647300,76.647300
XS GIS Cut Line= 4
1188009.07180062835010.4146646261187941.79749507 834779.29487294
1187917.92596725834715.275775731 1187721.5283978834537.324386835
#Sta/Elev= 30
9739.213102.5739 9744.37101.65859747.78799.809589758.03889.485739771.70688.52248
9792.20882.608079805.87680.191369840.04676.542359863.668 74.87179874.21675.17584
9891.30171.644449922.05471.121619976.726 64.11349987.15263.6330510025.6765.60671
10055.8365.0507210114.4665.8989510127.1567.3774310140.4370.0390510149.28 72.8774
10158.1477.3700710162.5678.3283910189.1376.7977110197.9877.3823610220.1286.80984
10242.2692.4771810264.39 101.66710295.25121.514510304.24 124.39610313.28 129.326
#Mann= 3 , 0 , 0
9739.213    0.12       09739.213    0.12       010313.28    0.12       0
#XS Ineff= 2 , 0
       0                10046.43       0
Bank Sta=9739.213,10313.28
Exp/Cntr=0.3,0.1

Type RM Length L Ch R = 1 ,2752.672,99.118600,99.118600,99.118600
XS GIS Cut Line= 6
1188248.88411598834951.5405019171188127.71905236834832.479598318
1188070.62267643834778.6844211351188012.97398962834728.247280183
1187894.54280057834630.3546310741187730.52814133834478.674989356
#Sta/Elev= 30
 9649.01118.03159666.014115.79459679.813108.71449712.505106.00769744.209107.7861
9763.996104.97199787.40199.023029804.00592.79878 9824.9887.911599862.902 82.5992
9880.93378.353169898.90976.514229929.42468.43426 9955.5863.336179989.968 63.0685
10011.1661.5447710041.0164.8767710095.0465.3175210117.7566.7651110148.5570.77954
10179.8477.2680310188.7977.2943910193.2478.3535810220.05 91.0759 10242.498.58637
10264.74 103.51410282.62116.730610287.08118.826310314.42126.046310350.98138.9403
#Mann= 3 , 0 , 0
 9649.01  0.1152       0 9649.01  0.1152       010350.98  0.1152       0
#XS Ineff= 2 , 0
       0                10046.38       0
Bank Sta=9649.01,10350.98
Exp/Cntr=0.3,0.1

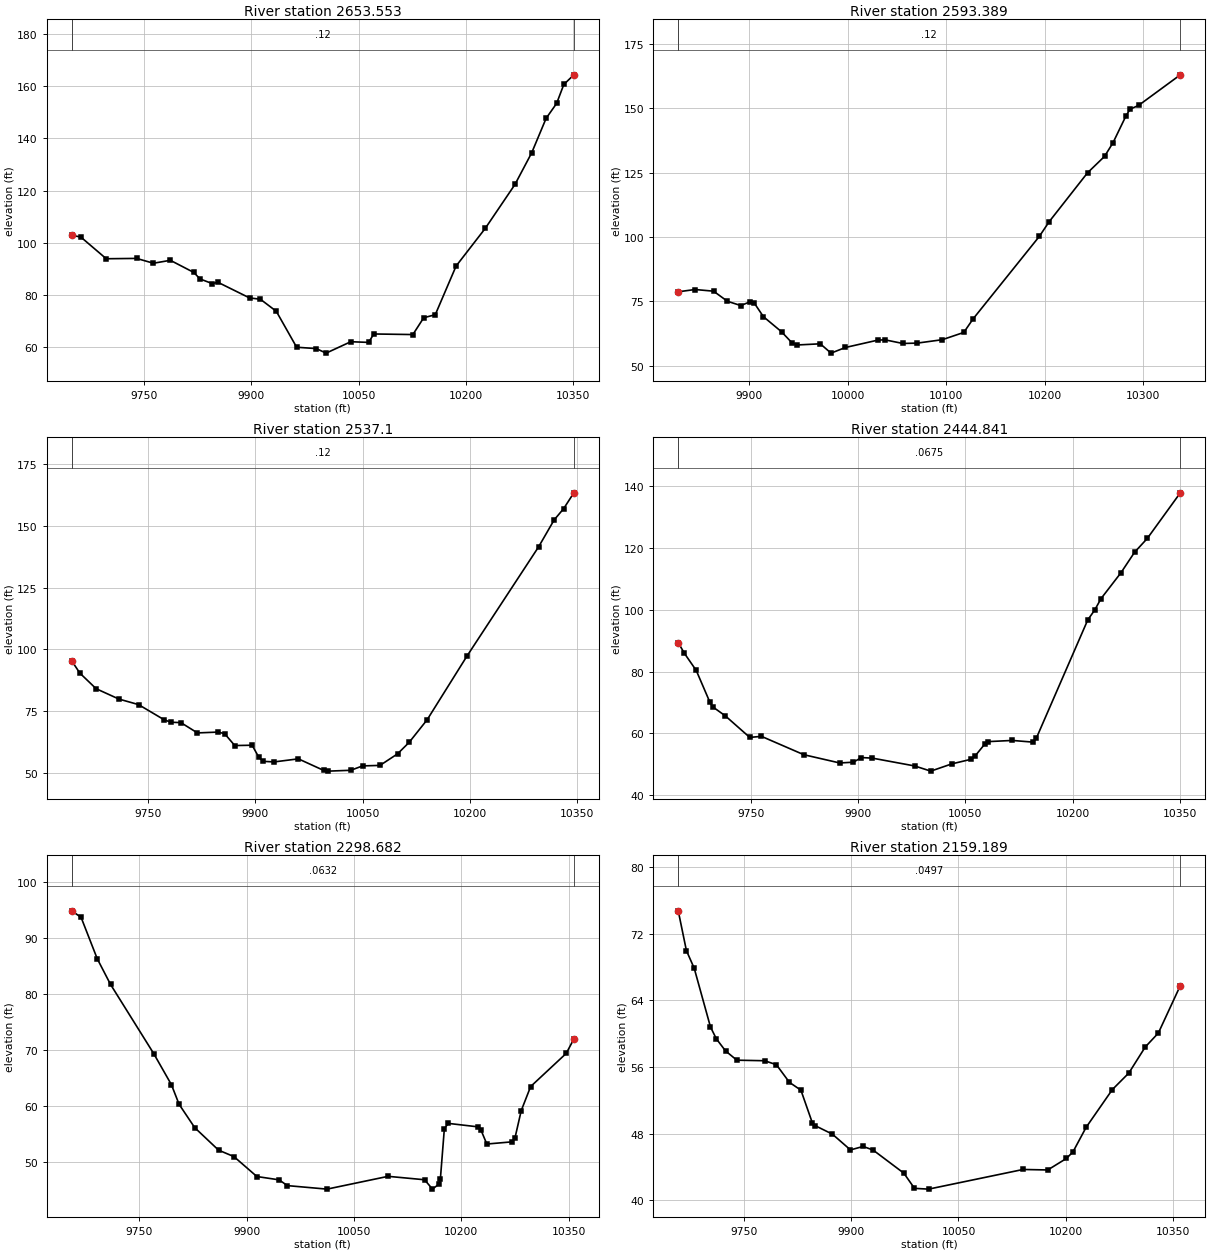
Type RM Length L Ch R = 1 ,2653.553,60.164400,60.164400,60.164400
XS GIS Cut Line= 6
1188307.99433491834825.7685962261188141.14195405834674.248113285
 1188084.8377816 834641.671557611187985.15287045834608.420544722
1187932.12054189834581.1702796721187741.66852337834425.373745048
#Sta/Elev= 30
9649.063102.85639661.465102.32439697.27193.955559739.68594.084569763.24992.23626
9786.86193.358169819.68988.709969828.38286.217919845.25284.466679853.49284.92594
9897.57778.966449912.75878.456239934.97173.847569963.41560.082269990.84359.57014
10004.6157.8293210039.1262.1949410064.0761.9360810071.2765.1623910125.8964.93593
10141.0771.3753610157.2272.5354110186.3791.1802210227.16105.605110268.61122.3804
10292.01134.502110312.16147.694110326.93153.444410336.91 160.66810350.94164.3555
#Mann= 3 , 0 , 0
9649.063    0.12       09649.063    0.12       010350.94    0.12       0
#XS Ineff= 2 , 0
       09939.588        10040.86       0
Bank Sta=9649.063,10350.94
Exp/Cntr=0.3,0.1

Type RM Length L Ch R = 1 ,2593.389,56.288700,56.288700,56.288700
XS GIS Cut Line= 4
1188183.76798117834679.4684840741188086.11173114 834583.98237294
1187908.16034228834498.2618868351187774.69680062834384.329595163
#Sta/Elev= 30
9827.94578.737789845.01279.627659863.78378.980139877.86175.055689891.49373.38209
 9900.6774.845079905.25974.273259914.43669.05422 9932.79 63.19919943.56158.83505
9948.25458.060299972.11458.520019983.03854.898639997.605 57.089810030.3859.94407
10037.6660.0758910055.8758.6557510070.4458.7884210095.9360.1150810117.7862.94649
10127.3168.2554710194.41100.259910204.51106.034110243.33124.978210260.59131.3586
10269.22136.678810282.16146.938410286.47149.7178 10295.1151.169310337.53163.0765
#Mann= 3 , 0 , 0
9827.945    0.12       09827.945    0.12       010337.53    0.12       0
#XS Ineff= 2 , 0
       0 9965.73        10040.34       0
Bank Sta=9827.945,10337.53
Exp/Cntr=0.3,0.1

Type RM Length L Ch R = 1 ,  2537.1,92.259100,92.259100,92.259100
XS GIS Cut Line= 6
1188346.31177916834770.7654304421188230.30559365834650.541903602
1188174.12569129834596.7185868391188075.10113291834512.583621951
1187953.82716123834420.3482291191187822.38250636 834305.24525792
#Sta/Elev= 30
9643.33495.32135 9654.6490.372669677.36584.065789709.27979.863629736.63377.63186
9772.76271.433259782.21270.476179795.90270.326799819.03266.154699847.48666.48607
9856.971 65.87569871.19961.037039895.49761.165779904.83156.298059910.96854.63326
9926.43954.412189960.11355.650829995.30451.0012210002.1450.67678 10033.451.01922
10049.9552.7938610074.2452.9953610098.7557.6632410115.0962.3556810140.21 71.5045
10195.69 97.206410295.99 141.517 10317.8152.474210330.88156.940910345.27163.4061
#Mann= 3 , 0 , 0
9643.334    0.12       09643.334    0.12       010345.27    0.12       0
#XS Ineff= 2 , 0
       09958.789        10095.02       0
Bank Sta=9643.334,10345.27
Exp/Cntr=0.3,0.1

Type RM Length L Ch R = 1 ,2444.841,146.158900,146.158900,146.158900
XS GIS Cut Line= 6
1188345.40278453834723.2095003441188240.79065132834598.874824511
1188152.45178543834457.8147170061188097.32467876834417.977798946
1187972.02631847834284.4596082981187885.56924636834199.511318665
#Sta/Elev= 30
  9648.889.356279657.46185.876529673.99880.336629692.64970.273469697.04868.56104
9714.64265.64337 9748.7758.676429765.13859.015379824.323 53.07549874.55850.40067
9893.515 50.65129904.88952.155529920.05451.970499979.23349.4359310001.8247.76031
10031.17 50.105810058.2751.6000410063.9852.7297410077.4756.5710710082.2457.31564
 10115.857.6946110144.9657.1402610149.4658.4908510221.2896.7380310230.8199.85721
10239.85103.6315 10267.6111.966910286.67118.6157 10304.4123.071210350.58137.8428
#Mann= 3 , 0 , 0
  9648.8  0.0675       0  9648.8  0.0675       010350.58  0.0675       0
#XS Ineff= 2 , 0
       09869.495                       0
Bank Sta=9648.8,10350.58
Exp/Cntr=0.3,0.1

Type RM Length L Ch R = 1 ,2298.682,139.493200,139.493200,139.493200
XS GIS Cut Line= 6
1188492.04615528834712.3682781461188406.53038145834627.072816619
1188342.25654343834551.3184044721188298.69747527834486.566069552
1188204.76246957834317.6248436691188068.59597074834157.879248362
#Sta/Elev= 30
9655.44594.863579668.47993.694179691.05386.294359709.63781.703899770.03269.33317
 9794.7663.775089805.45760.27471 9827.3856.088039860.66952.07108 9882.1350.92042
9914.23147.354389945.30746.762659956.82445.7312810012.2445.1023410097.7147.38986
10148.6246.7781510159.68 45.117310168.9646.0072610170.7846.9429910176.3355.93985
10181.8856.8566510223.0356.2427710227.2655.73478 10235.753.1661810270.5853.55224
10274.9754.2144810283.7759.1313110296.9763.4473410346.6769.3702510357.3571.93906
#Mann= 3 , 0 , 0
9655.445  0.0632       09655.445  0.0632       010357.35  0.0632       0
#XS Ineff= 2 , 0
       0                               0
Bank Sta=9655.445,10357.35
Exp/Cntr=0.3,0.1

Type RM Length L Ch R = 1 ,2159.189,100.347400,100.347400,100.347400
XS GIS Cut Line= 6
1188663.23273031 834552.992364221188475.66312765834416.097737908
 1188328.6704975834333.3095142121188297.35337217834312.120802808
1188247.59728142834267.3889473151188110.34325105834127.245482351
#Sta/Elev= 30
9658.211 74.73389669.62769.965299680.56867.838219703.27260.796159711.47259.37452
9724.33257.922889740.17156.808269779.03856.74229 9795.4556.264629813.70554.14476
 9829.7153.210529845.71649.283049849.71748.947099873.72547.932249899.01546.03998
9916.67746.45405 9930.4646.03419 9973.62 43.24869988.50541.4262210008.1941.33368
10140.3543.6929610174.7843.6332210200.8745.0131210210.0645.8024110228.4248.74558
10265.1653.2865410288.1255.2619710311.0858.3870510329.45 60.070610360.1365.75921
#Mann= 3 , 0 , 0
9658.211  0.0497       09658.211  0.0497       010360.13  0.0497       0
#XS Ineff= 2 , 0
       0                               0
Bank Sta=9658.211,10360.13
Exp/Cntr=0.3,0.1