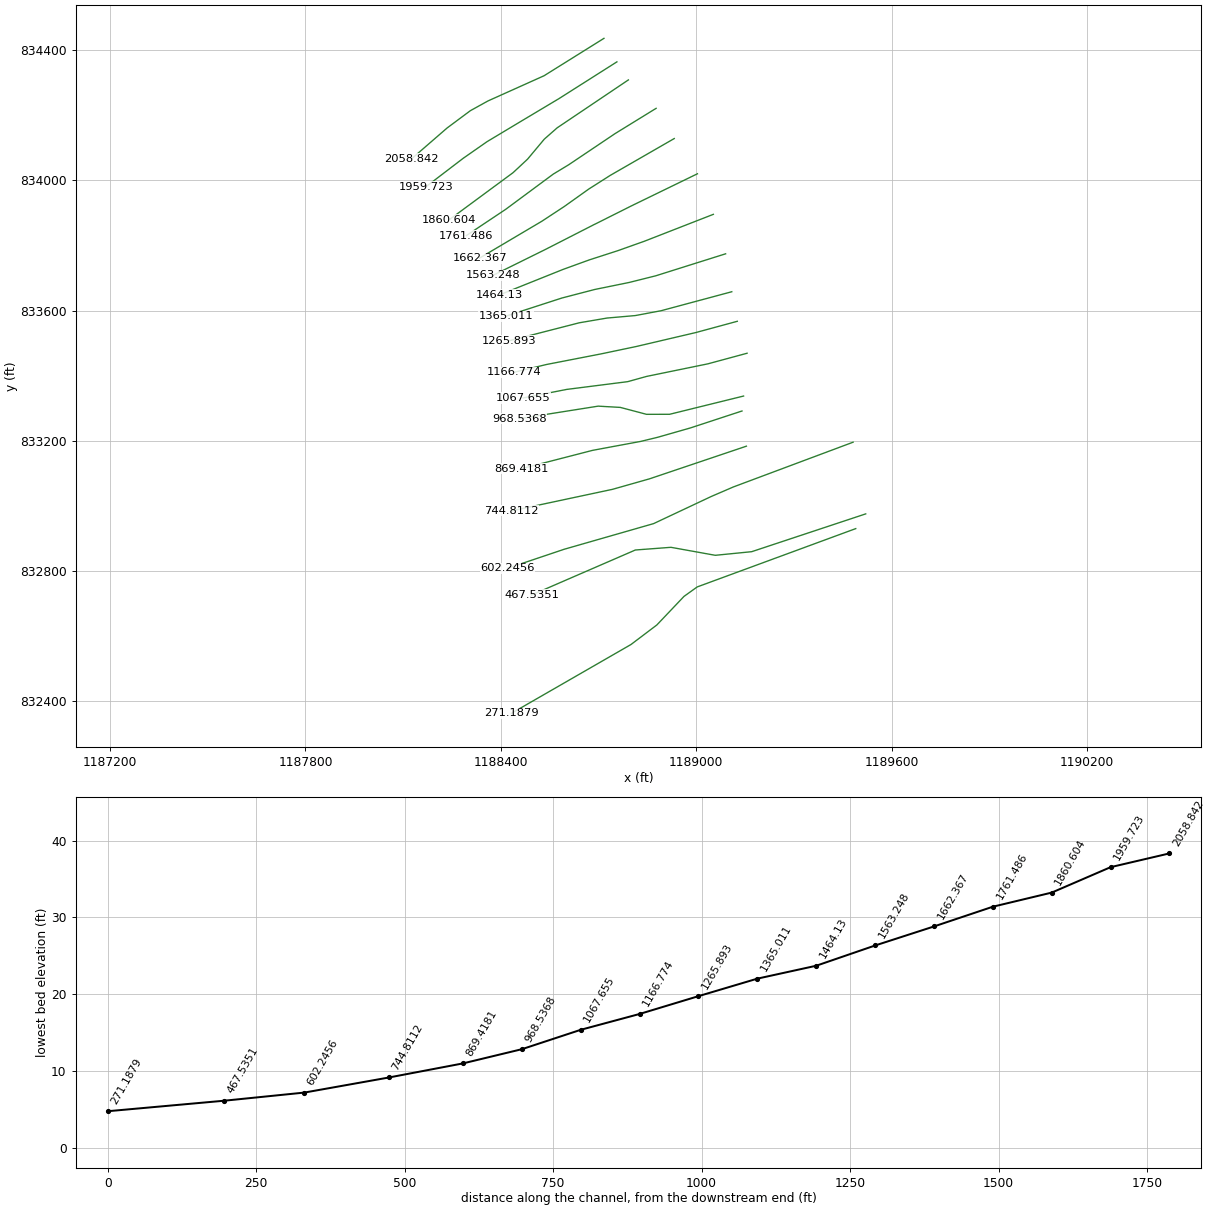
HEC-RAS study 25_ras.prj: 25

--- 25_ras.g01 (geometry) --- (continued)

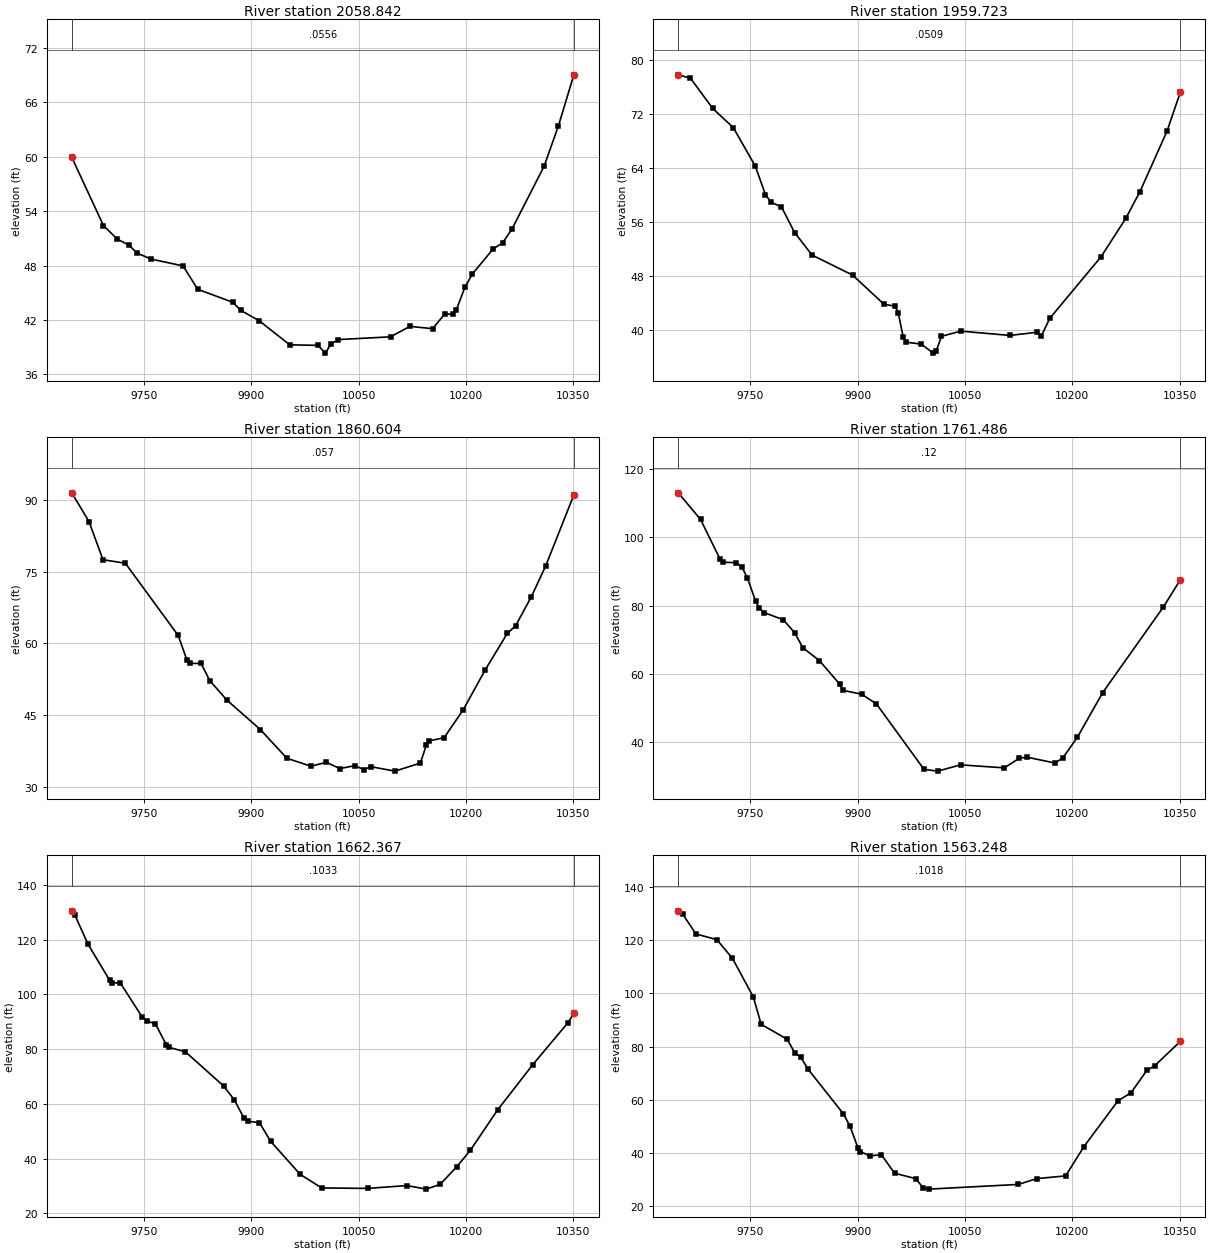
Type RM Length L Ch R = 1 ,2058.842,99.118700,99.118700,99.118700
XS GIS Cut Line= 6
1188716.72934124 834436.524780791188532.83719719834321.679432884
1188360.48185853834244.2285938071188306.52880334834214.412911501
1188234.98838415834161.2026668161188125.30589723834066.124405564
#Sta/Elev= 30
9649.04159.954129693.33452.422199712.93950.912819728.62450.286459740.38749.38759
9759.99248.725339804.67947.973989825.05145.399539874.13143.960579885.10443.08006
9910.70841.943449953.87539.269079993.01739.2117310003.7438.35481 10010.939.33029
10021.6539.8487410094.6940.1525110121.7441.3053110153.5641.0502810170.1842.64465
 10182.742.6607710186.8843.1632510198.75  45.63110209.1747.0823810238.2149.85665
10251.2450.5014410264.2652.0068210309.3458.9571610329.3863.4076410350.9769.04671
#Mann= 3 , 0 , 0
9649.041  0.0556       09649.041  0.0556       010350.97  0.0556       0
#XS Ineff= 2 , 0
       0                               0
Bank Sta=9649.041,10350.97
Exp/Cntr=0.3,0.1

Type RM Length L Ch R = 1 ,1959.723,99.118600,99.118600,99.118600
XS GIS Cut Line= 6
1188756.42054885834364.2942977561188577.79672266834250.931563378
1188458.94297169834179.9607308941188358.08036516834119.486849949
1188284.90339803834068.4850787611188169.53813114833980.369116495
#Sta/Elev= 30
9649.00977.870189666.08477.380649697.17172.886249725.98270.031359756.596 64.3519
    977160.083649778.772 58.94529793.33258.278879811.70154.455519836.19251.10758
9892.68548.151859936.80143.797879952.08643.550239956.67842.51049 9963.5538.91852
9967.37138.184839988.67537.90518 10005.636.5610110009.4236.8318410017.0739.05241
10043.8539.82689 10112.739.1898210150.7739.6603510156.5139.0683510168.5141.73036
10240.4450.9029910274.6456.5465810294.4960.5193710332.4469.5223510350.9775.28764
#Mann= 3 , 0 , 0
9649.009  0.0509       09649.009  0.0509       010350.97  0.0509       0
#XS Ineff= 2 , 0
       0                               0
Bank Sta=9649.009,10350.97
Exp/Cntr=0.3,0.1

Type RM Length L Ch R = 1 ,1860.604,99.118600,99.118600,99.118600
XS GIS Cut Line= 6
1188791.71350553 834308.860010351188573.07420997834161.748713828
1188533.37991193834126.8536658151188482.06271281834065.446784522
1188437.80205992834024.196333248 1188240.7793298833878.905986772
#Sta/Elev= 30
9649.081 91.5709 9673.1485.555289692.69477.554769723.98276.813269797.81261.68549
9810.02256.548079813.93355.821139829.82955.820279841.95952.221059866.21948.08514
9912.67641.958269949.85135.931279983.60634.2732810005.0235.0955910023.7933.78049
10044.3734.37722 10057.533.5852210067.1334.1747310100.8133.2451910136.3534.92542
10144.6738.6699810148.2639.5724110169.5940.2514610196.2746.0931110227.1454.49209
10258.0562.14686 10269.463.68206 10291.569.7925510311.6176.2721310350.9291.12145
#Mann= 3 , 0 , 0
9649.081   0.057       09649.081   0.057       010350.92   0.057       0
#XS Ineff= 2 , 0
       0                               0
Bank Sta=9649.081,10350.92
Exp/Cntr=0.3,0.1

Type RM Length L Ch R = 1 ,1761.486,99.118700,99.118700,99.118700
XS GIS Cut Line= 6
1188876.83119969834221.5475433021188750.99832925834144.075897161
1188608.41886417834048.2897368551188561.09956717834019.658014177
1188414.88643468833911.3758894151188294.14287497833830.823154541
#Sta/Elev= 30
9649.024113.11219680.214105.31239707.18393.777229711.99292.74431  9730.392.58978
9738.00591.336939745.71188.141459757.26981.279269762.05579.267089768.82877.97251
9795.79775.863439811.58172.090969823.43867.58959  9846.563.83398 9874.8256.92762
9878.77355.146699905.33353.999549926.20251.123089992.66231.9103510011.81 31.4055
10043.7133.2460810104.9532.36324   1012635.2174110137.0235.4811310175.6133.79407
 10186.635.2428910206.9741.3143410242.4754.4678110327.1379.5374510350.9687.57466
#Mann= 3 , 0 , 0
9649.024    0.12       09649.024    0.12       010350.96    0.12       0
#XS Ineff= 2 , 0
       0                               0
Bank Sta=9649.024,10350.96
Exp/Cntr=0.3,0.1

Type RM Length L Ch R = 1 ,1662.367,99.118600,99.118600,99.118600
XS GIS Cut Line= 6
 1188932.5200568834128.8058247911188735.53884094834015.365461451
 1188669.6387626 833973.413586121188595.45195517833920.522437059
1188526.43272307833875.1343261741188334.72467996833761.643604998
#Sta/Elev= 30
9649.017130.5186 9653.04129.12059671.853118.27889701.954105.14539705.717104.2484
9717.005104.11819747.10591.859019754.63190.202359765.91889.258619781.13381.61796
9784.94580.628749807.82379.029179861.20366.535649876.45761.408699889.89254.68294
9895.90353.61258 9911.4653.103259927.01746.306049968.29234.238339998.40929.26664
10062.5829.0936810117.5530.1382810144.7128.8313210163.9530.5525210187.0436.93572
10206.28 43.011610244.4757.8062310293.68 74.352210342.8989.6810710350.9893.02755
#Mann= 3 , 0 , 0
9649.017  0.1033       09649.017  0.1033       010350.98  0.1033       0
#XS Ineff= 2 , 0
       0                               0
Bank Sta=9649.017,10350.98
Exp/Cntr=0.3,0.1

Type RM Length L Ch R = 1 ,1563.248,99.118600,99.118600,99.118600
XS GIS Cut Line= 6
1189003.76124169834020.6309437321188801.46905552833922.222728786
1188689.71696602833866.1375628791188687.87630416833865.355281651
1188537.14459176833788.305077301 1188375.1315426833708.255726826
#Sta/Elev= 30
9649.005131.05319655.513129.71069673.756122.34799702.943120.21279724.834113.1661
9754.02198.625029764.96788.354099801.45182.712919812.39677.378749820.17376.07185
9830.63971.425349880.01954.657589889.10650.049439900.11942.003439903.78940.47698
 9916.5938.884319933.15639.24662 9951.5132.329939980.87730.309149991.889 26.7386
9999.22426.3496910124.44 28.119810150.2330.3007910190.6331.3279810216.2442.35401
10263.8159.5618310282.1162.6178610304.0770.9826210315.0572.7304210350.9981.92185
#Mann= 3 , 0 , 0
9649.005  0.1018       09649.005  0.1018       010350.99  0.1018       0
#XS Ineff= 2 , 0
       0                               0
Bank Sta=9649.005,10350.99
Exp/Cntr=0.3,0.1

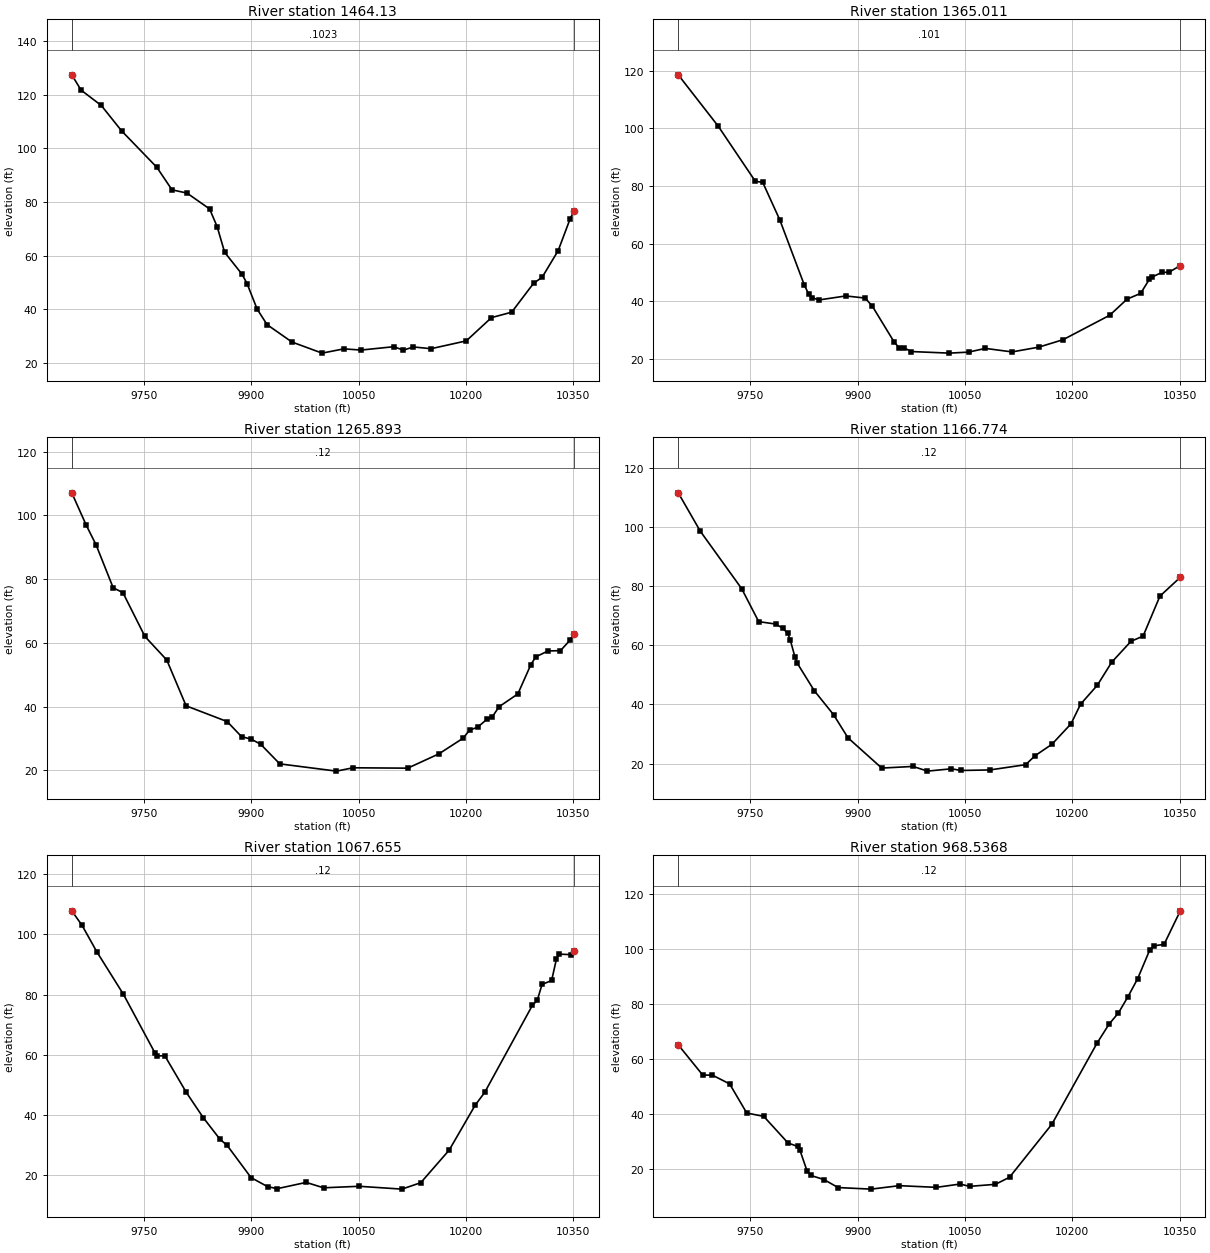
Type RM Length L Ch R = 1 , 1464.13,99.118600,99.118600,99.118600
XS GIS Cut Line= 6
1189052.65310429833896.0519179181188841.39367548833813.637201866
1188759.99918852833784.6665343791188671.73551982833756.152379181
 1188590.9255848833726.8296005131188395.92770705833648.674317155
#Sta/Elev= 30
9649.008127.33139662.036121.63219690.311115.91539718.587106.49339768.04692.86699
9789.09884.51935 9810.1583.294499841.72877.392869852.25470.80417 9862.7861.23365
9887.25553.01697 9894.2249.51903 9908.1540.119169922.07934.313169956.90427.83517
    999923.7098310029.3425.2977210053.4924.8521210098.8526.0899910112.8124.85039
10126.7726.0085410151.2925.3540210200.5828.2720510235.7936.9281310264.0838.95487
10294.6849.7100710306.6851.9601410329.0761.8695510345.7273.6704110350.9976.45216
#Mann= 3 , 0 , 0
9649.008  0.1023       09649.008  0.1023       010350.99  0.1023       0
#XS Ineff= 2 , 0
       0                               0
Bank Sta=9649.008,10350.99
Exp/Cntr=0.3,0.1

Type RM Length L Ch R = 1 ,1365.011,99.118700,99.118700,99.118700
XS GIS Cut Line= 6
1189090.28732895833774.834079301 1188875.6720316833707.247431723
1188793.75936577833686.7625653521188688.18187948833665.230767582
1188587.51720301833639.0542019651188415.63328004833583.380404826
#Sta/Elev= 30
9649.024118.54299704.936100.73199756.84481.606439767.13481.258269791.08168.20198
9825.29145.649839831.25842.581499835.55441.300889845.81740.469769883.34141.85956
9910.39641.124869920.541 38.24729950.97825.843219957.74223.924459964.43923.94664
9974.472 22.580110028.0322.0276510054.8422.3732810078.4423.6673410115.7322.44835
10153.0224.0985510187.1126.6921310252.2735.1655910276.5340.7515410295.4942.74494
10307.7247.6366210311.1948.3843910325.0550.0054310335.4550.1123410350.9752.40668
#Mann= 3 , 0 , 0
9649.024   0.101       09649.024   0.101       010350.97   0.101       0
#XS Ineff= 2 , 0
       0                               0
Bank Sta=9649.024,10350.97
Exp/Cntr=0.3,0.1

Type RM Length L Ch R = 1 ,1265.893,99.118600,99.118600,99.118600
XS GIS Cut Line= 6
 1189109.2166615 833658.338834571188892.00108646833599.996313958
 1188812.9605299833585.1567508791188726.24510136 833577.56324175
1188640.83653877833562.9645626411188425.12552275833507.546861707
#Sta/Elev= 30
9649.064107.06689669.31996.90187 9682.9990.773099706.91377.293159720.58475.72917
9751.34361.990589781.86854.613779808.89540.236529866.32535.290379886.44630.55653
9899.79829.793869913.15128.172229939.85622.0231310019.1119.7455110042.1620.79379
10118.7120.6751310162.3925.1742210196.0730.0688410205.3232.6391610216.2833.49832
10229.7536.0657710236.49 36.6549 10246.639.9817910272.6443.9642310290.9353.18881
10297.7555.6083810314.8257.4486210332.2757.5481510345.5360.8209710350.9462.92517
#Mann= 3 , 0 , 0
9649.064    0.12       09649.064    0.12       010350.94    0.12       0
#XS Ineff= 2 , 0
       0                               0
Bank Sta=9649.064,10350.94
Exp/Cntr=0.3,0.1

Type RM Length L Ch R = 1 ,1166.774,99.118600,99.118600,99.118600
XS GIS Cut Line= 6
1189126.15456062833567.5704855241188999.01395116 833533.07429772
1188816.16778727833490.2156332381188707.12360135833467.324035354
1188541.33957621833435.149496073  1188441.992717833411.453845892
#Sta/Elev= 30
9649.013111.70159679.91298.683439737.70379.234879761.49968.068499785.25567.24671
9795.36565.803599802.10464.055819805.47462.000329812.21356.084829815.58353.92467
9839.17144.687339866.12936.559469886.348 28.70829933.52518.456629977.29719.01368
9997.43617.4231510030.9518.2159310044.3517.6461710084.5517.8208110134.6819.59921
10148.0522.6667410171.4426.5102810198.1833.4482810211.5540.1002110234.9446.50444
10255.0554.3135310282.0361.40163 10298.963.1487210322.5176.7091510350.9983.08559
#Mann= 3 , 0 , 0
9649.013    0.12       09649.013    0.12       010350.99    0.12       0
#XS Ineff= 2 , 0
       0                               0
Bank Sta=9649.013,10350.99
Exp/Cntr=0.3,0.1

Type RM Length L Ch R = 1 ,1067.655,99.118600,99.118600,99.118600
XS GIS Cut Line= 6
  1189156.214637833469.4755032621189035.87537255833436.929890598
1188847.98142829833398.3863617671188789.57793366833382.199649783
1188602.45831908833358.4093659271188468.86654112833332.235008461
#Sta/Elev= 30
9649.044107.81729663.494102.96589683.88694.273429721.27280.075989765.45560.54938
9768.85459.570579778.99159.714919809.24447.464559832.77439.13347 9856.2431.92106
9866.26829.886239899.69119.177519923.08816.145589936.45815.523179976.77117.59144
   1000115.7982110050.9516.3014610110.4815.3576710136.9317.4941310176.6228.31004
   1021343.2427810226.3147.4986110293.0276.4329810299.7378.0568110306.4483.34758
10319.8784.6852310326.58 91.791410329.9493.4356410346.7293.2609610350.9294.36138
#Mann= 3 , 0 , 0
9649.044    0.12       09649.044    0.12       010350.92    0.12       0
#XS Ineff= 2 , 0
       0                               0
Bank Sta=9649.044,10350.92
Exp/Cntr=0.3,0.1

Type RM Length L Ch R = 1 ,968.5368,99.118700,99.118700,99.118700
XS GIS Cut Line= 6
 1189145.4611295833338.0185455311188918.26181809833281.975627176
1188847.35826535833281.8701556831188766.91402813833303.137070252
1188698.86467376833306.9956286711188457.40634975833268.698628864
#Sta/Elev= 30
9649.08665.160329683.26754.225399696.975 54.16179720.96450.992439744.85940.43385
9768.61639.220559802.48929.591529815.90128.314139819.25326.911449829.31219.30599
9834.47217.78383  9852.716.312199872.58113.398529918.67412.830299958.16214.08278
10009.9913.4753810043.0914.67643 10056.313.8363210092.4614.5672710112.16 17.1361
10171.4636.3943710234.4565.7472310251.1572.6130310264.5176.7717810277.8782.67733
10291.2389.1304510308.0199.4688210314.74101.120910328.21101.607510350.93113.7819
#Mann= 3 , 0 , 0
9649.086    0.12       09649.086    0.12       010350.93    0.12       0
#XS Ineff= 2 , 0
       0                               0
Bank Sta=9649.086,10350.93
Exp/Cntr=0.3,0.1

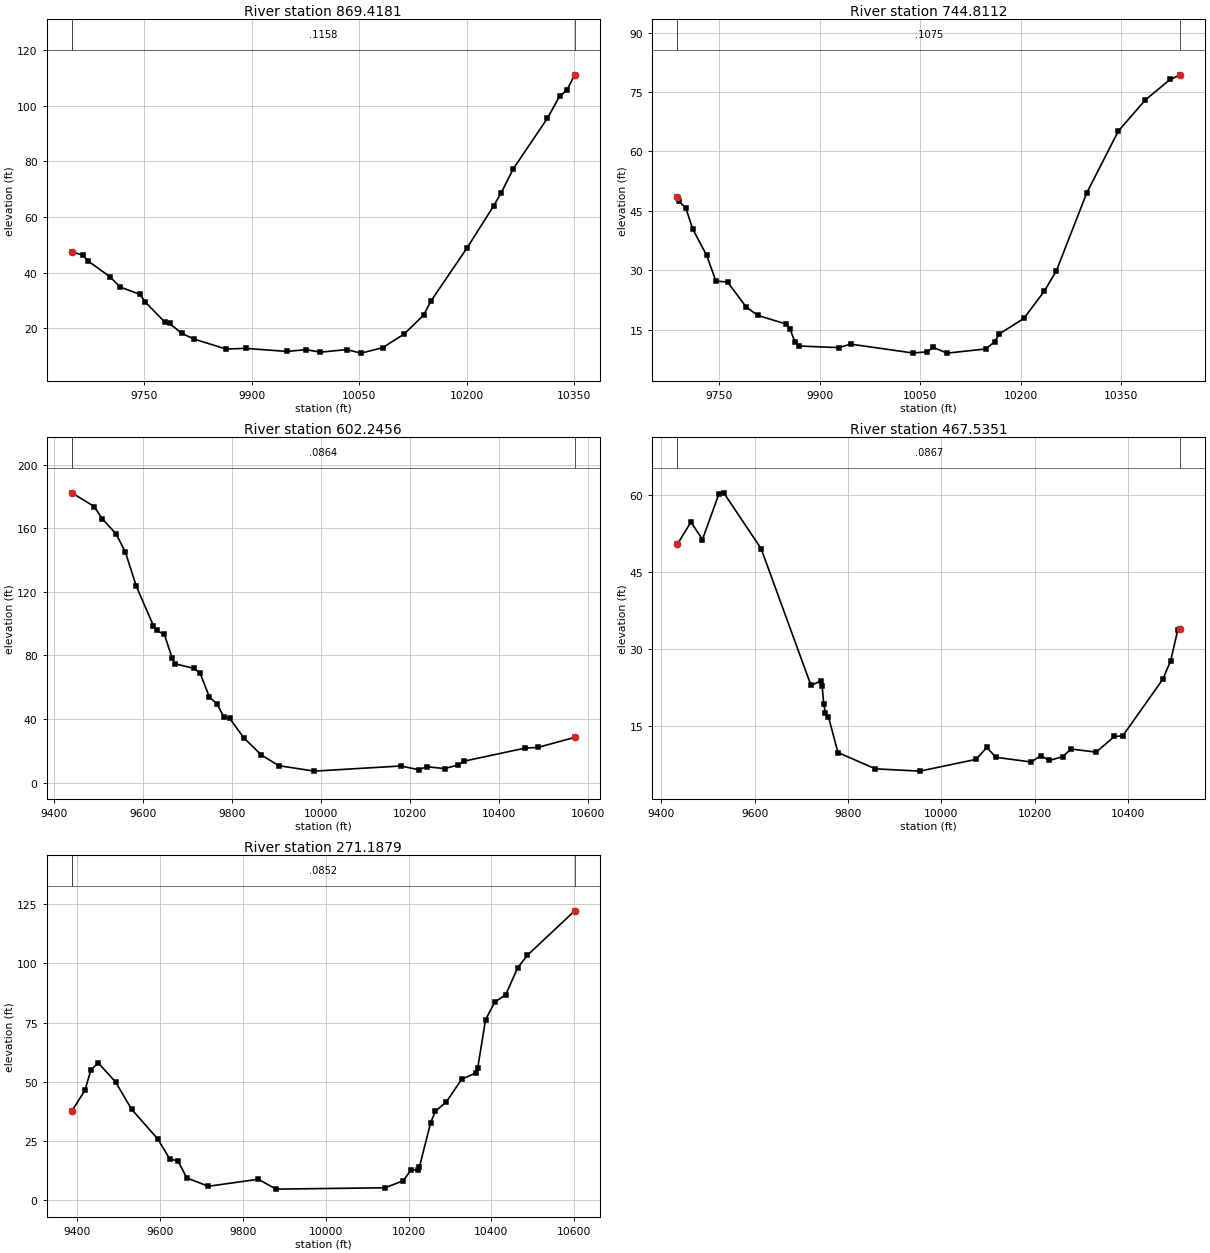
Type RM Length L Ch R = 1 ,869.4181,124.606900,124.606900,124.606900
XS GIS Cut Line= 6
1189140.59013127833292.1077610071188982.05818667833240.045369965
1188881.91417444833211.4370115361188829.62968595833198.735047465
1188681.70505889833171.2436494071188462.33823997833114.676607785
#Sta/Elev= 30
9649.03547.451829664.53846.251479671.44444.205449702.52338.454869716.33634.80305
9743.96232.151089751.75229.325659778.49422.242769785.40121.657099802.66718.09162
9819.88516.017959864.24212.458499891.53912.683889949.23411.591599976.20112.22609
9996.08811.3173610032.5312.2511610052.6410.9783910082.86 12.924610113.0717.89457
10140.0224.6234110150.1529.6864410200.8148.9071710237.9664.0715410248.1468.58458
10265.1477.3299810312.7595.5132310329.75103.457710339.95105.675510350.97111.2164
#Mann= 3 , 0 , 0
9649.035  0.1158       09649.035  0.1158       010350.97  0.1158       0
#XS Ineff= 2 , 0
       0                               0
Bank Sta=9649.035,10350.97
Exp/Cntr=0.3,0.1

Type RM Length L Ch R = 1 ,744.8112,142.565600,142.565600,142.565600
XS GIS Cut Line= 4
 1189154.0917567 833184.070718851188856.72536403833083.815763588
1188742.87651652833051.5302695281188431.91623163832985.260044883
#Sta/Elev= 30
9687.762 48.45349689.85647.401049700.24345.810149710.629 40.45039731.403 33.8099
9745.25227.301829762.56427.081269790.26220.807349807.57318.665189850.41716.46037
9856.04515.11225 9862.9712.043779869.89410.932219928.75310.530629946.06411.41048
10038.979.18271110059.44 9.4646110069.6710.5667910090.139.14286910147.6410.19526
10161.0612.0064310167.7713.9534310204.6717.9151810234.86 24.732410252.7729.78518
10298.5949.6310510345.5665.1721610385.8173.0075810422.7178.1543910437.86 79.3312
#Mann= 3 , 0 , 0
9687.762  0.1075       09687.762  0.1075       010437.86  0.1075       0
#XS Ineff= 2 , 0
       0                               0
Bank Sta=9687.762,10437.86
Exp/Cntr=0.3,0.1

Type RM Length L Ch R = 1 ,602.2456,134.710500,134.710500,134.710500
XS GIS Cut Line= 6
1189481.82245205833196.3067606061189114.35308231833058.965950559
1189045.52198317833029.2714281811188869.14952604832946.275099232
1188594.72813949832867.5561107051188420.70796816832808.978229238
#Sta/Elev= 30
9439.354182.2278 9490.06173.53969507.548 165.9639539.027156.34579560.013144.8524
9584.496 123.438 9622.9798.623769629.96595.663299647.45493.183789664.94278.48662
9671.93774.700169713.909 71.80759727.90768.778449749.00353.737419766.58449.33491
9780.64841.420539794.71240.291829826.356 28.06899865.57517.379969904.87910.61514
9984.8557.17332910179.6210.4076810220.398.02044410237.379.94874610278.158.771098
10308.8511.0799710322.53  13.49210459.9221.7046510487.5422.0664510570.7428.39643
#Mann= 3 , 0 , 0
9439.354  0.0864       09439.354  0.0864       010570.74  0.0864       0
#XS Ineff= 2 , 0
       0                               0
Bank Sta=9439.354,10570.74
Exp/Cntr=0.3,0.1

Type RM Length L Ch R = 1 ,467.5351,196.347200,196.347200,196.347200
XS GIS Cut Line= 6
1189520.51669843832976.152271488  1189170.337178832860.044599463
1189058.59522264832848.9394984761188922.40063699832873.468505128
1188813.10825893832865.2323729541188494.42867503832726.997189188
#Sta/Elev= 30
9434.33150.38144 9463.4554.720049488.03451.287459523.15460.14494 9533.6960.40414
9613.80649.510889720.77422.821269741.33323.70002 9744.7122.626849748.08719.12289
9751.46417.544119758.21816.67364 9778.489.7481039858.572 6.562359954.026 6.11436
10074.478.40949510097.4410.7301910117.248.80997210192.237.90069910213.699.132957
10231.578.20346310260.188.93143410278.0610.43097 10331.79.81256710371.0412.87584
10388.9212.9964210474.7524.0363310491.73 27.680310506.9333.7223810512.1633.84797
#Mann= 3 , 0 , 0
9434.331  0.0867       09434.331  0.0867       010512.16  0.0867       0
#XS Ineff= 2 , 0
       09886.292                       0
Bank Sta=9434.331,10512.16
Exp/Cntr=0.3,0.1

Type RM Length L Ch R = 1 ,271.1879,131.140200,131.140200,131.140200
XS GIS Cut Line= 6
1189489.92170422832930.9392433051189003.00173139832751.795306536
1188962.48022655832722.7427692131188879.07557253832634.994103525
1188799.57866021832574.9175768911188432.26379245 832363.50924003
#Sta/Elev= 30
 9387.1537.724349418.75346.422569432.85254.847319450.47658.125839492.77549.96127
9531.54838.433859594.99525.845799622.94417.624879643.82616.509169664.7089.460379
9716.8645.9476069837.547 8.906329879.7224.74248810142.99 5.3120510186.948.262479
 10206.412.9808410221.9712.7750110225.8713.9308310253.1232.69494 10264.637.57875
10291.2941.6271110328.2251.1358710363.2853.8656610367.0356.0623110385.7776.30034
10408.2683.71513 10434.586.8350210463.4398.2272410486.97103.529810600.95122.2358
#Mann= 3 , 0 , 0
 9387.15  0.0852       0 9387.15  0.0852       010600.95  0.0852       0
#XS Ineff= 2 , 0
       09821.969        10164.14       0
Bank Sta=9387.15,10600.95
Exp/Cntr=0.3,0.1