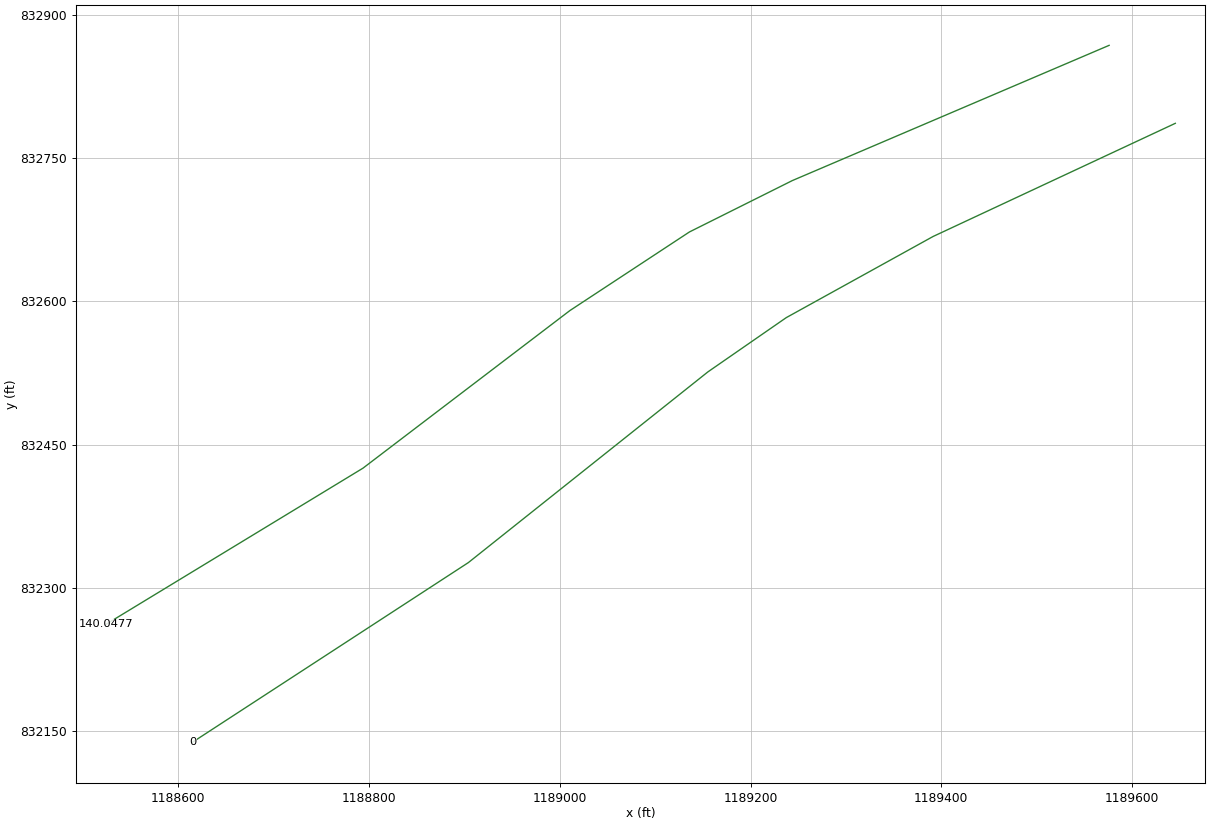
HEC-RAS study 25_ras.prj: 25

--- 25_ras.g01 (geometry) --- (continued)

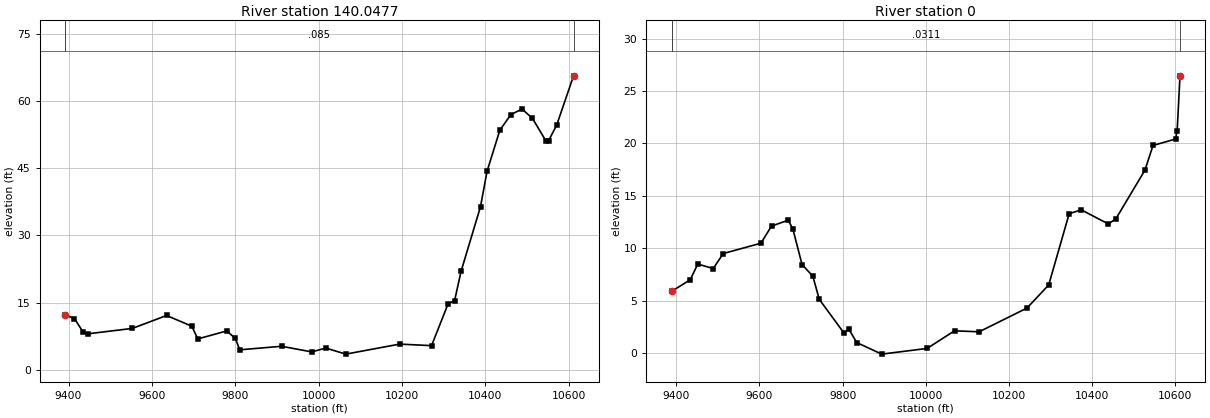
Type RM Length L Ch R = 1 ,140.0477,140.047700,140.047700,140.047700
XS GIS Cut Line= 6
1189576.04494726832868.1499996941189243.85154462832726.592185466
1189135.90565909832672.7841323171189010.55537887832590.500708272
1188793.57385356832425.5171949131188523.94018175832261.956603511
#Sta/Elev= 30
9392.02712.237099414.19611.417979435.5948.3083119446.8098.0137839553.2819.224393
9635.306 12.10819695.933 9.707759710.1986.8717689779.4628.6503579800.0717.007251
9810.9354.4376349911.3835.2287389983.6473.96730110017.414.833964 10065.23.472164
10194.75 5.7131910271.185.365687 10310.914.7367410326.4515.43359   1034221.99009
10388.6636.4464110404.2144.3044610435.0353.5226610461.6657.03078 10488.358.24632
 10513.356.1699110545.3951.1537110552.1551.2029510571.5754.6888910611.8665.67628
#Mann= 3 , 0 , 0
9392.027   0.085       09392.027   0.085       010611.86   0.085       0
#XS Ineff= 2 , 0
       0  9899.8        10109.63       0
Bank Sta=9392.027,10611.86
Exp/Cntr=0.3,0.1

Type RM Length L Ch R = 1 ,       0,0.000000,0.000000,0.000000
XS GIS Cut Line= 6
1189645.45809731 832786.520525261189391.37294913832668.024105803
1189237.44918164832583.0937506191189155.25083084 832526.27769399
1188904.08137668832326.6616323721188614.81301637832138.624848139
#Sta/Elev= 30
9388.899 5.88216 9433.546.9841039451.5798.4847629488.7918.0567279512.9119.488739
9603.47610.476159628.961 12.11179669.00812.66888 9680.1911.852719702.3548.436714
9728.2937.3291279743.7045.1209949803.2331.8953329814.6712.2858929833.7330.990093
9893.906-0.1169110003.160.42749310068.932.11187110128.152.01503310243.234.284164
10295.416.48912410344.6413.2963210373.7613.6623810439.0612.30753 10457.212.82512
10526.8617.4552810546.2119.8113810600.3920.4236310604.2621.21651 10611.126.46051
#Mann= 3 , 0 , 0
9388.899  0.0311       09388.899  0.0311       0 10611.1  0.0311       0
#XS Ineff= 2 , 0
       0 9922.17        10064.71       0
Bank Sta=9388.899,10611.1
Exp/Cntr=0.3,0.1